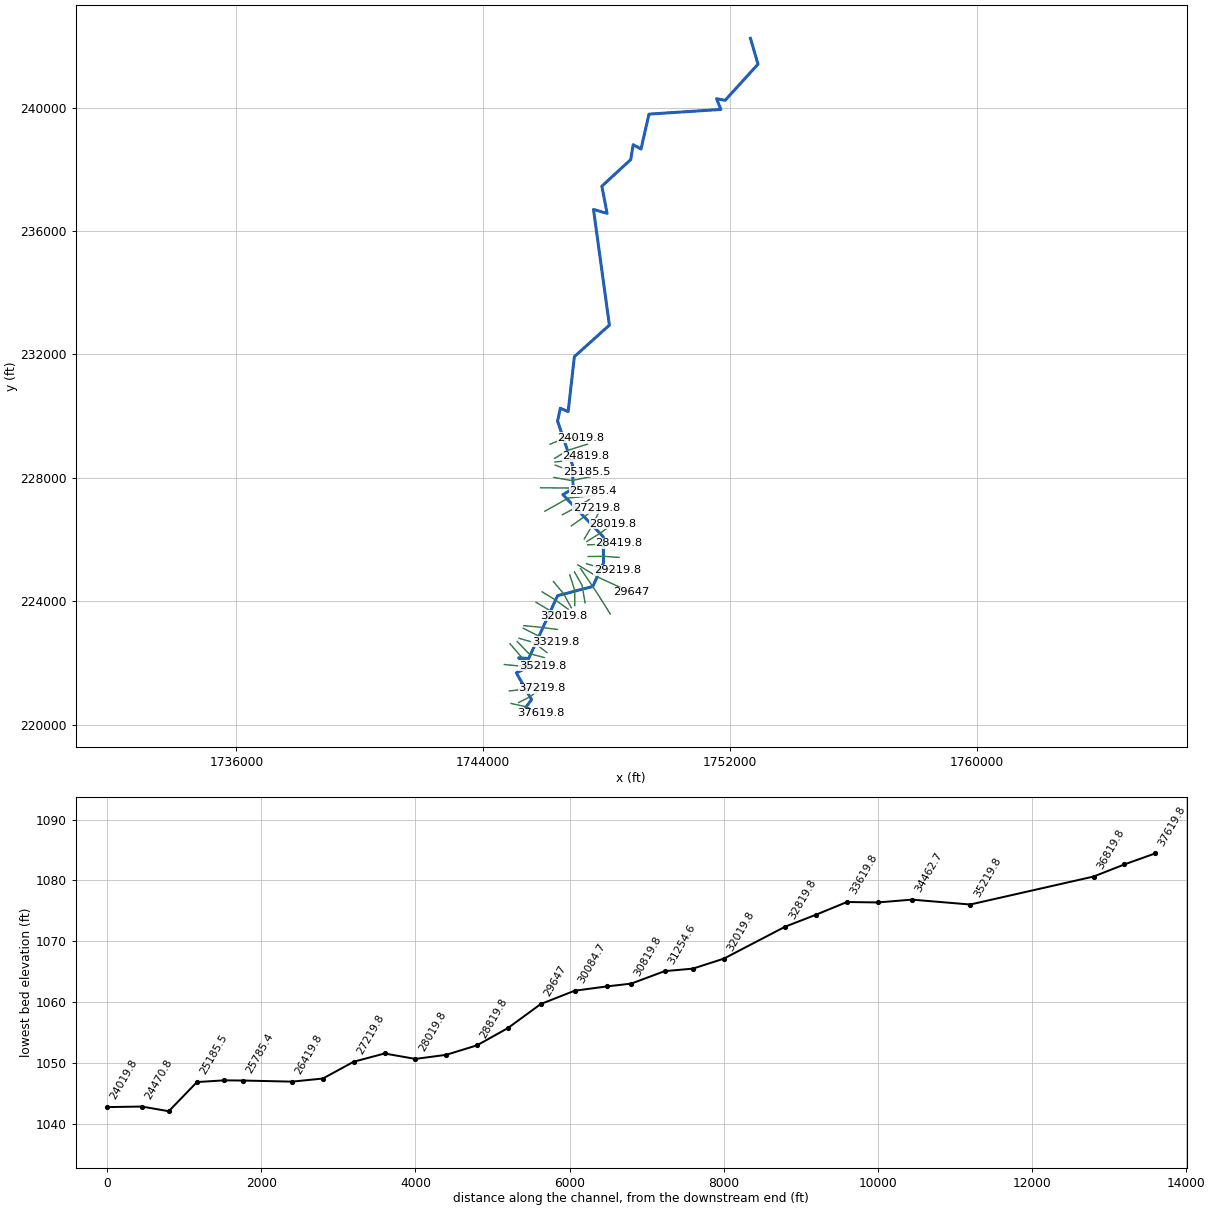
--- RotingCr.prj (project) ---

Proj Title=RotingCr
Current Plan=p01
Default Exp/Contr=0,0
English Units
Geom File=g01
Flow File=f01
Plan File=p01
BEGIN DESCRIPTION:
END DESCRIPTION:
DSS Export Rating Curves= 0
DSS Export Rating Curve Sorted= 0
DSS Export Volume Flow Curves= 0
DXF OffsetX= 0
DXF OffsetY= 0
DXF ScaleX= 0
DXF ScaleY= 0

--- RotingCr.p01 (plan) ---

Plan Title=Floodplain
Program Version=4.00
Geom File=g01
Flow File=f01
K Sum by GR=0
Std Step Tol=0.01
Critical Tol=0.01
Num of Std Step Trials=20
Max Error Tol=0.3
Flow Tol Ratio=0.001
Split Flow NTrial=30
Split Flow Tol=0.02
Split Flow Ratio=0.02
Log Output Level=0
Friction Slope Method=1
Unsteady Friction Slope Method=2
Unsteady Bridges Friction Slope Method=1
Global Log Level=0
CheckData=False
Run HTab=0
Run UNet=0
Run PostProcess=0
UNET Theta=0
UNET Theta Warmup=0
UNET ZTol=0
UNET ZSATol=0
UNET MxIter=0
UNET MaxInSteps=0
UNET DtIC=0
UNET DtMin=0
UNET MaxCRTS=0
UNET WFStab=0
UNET SFStab=0
UNET WFX=0
UNET SFX=0
UNET DSS MLevel=0
UNET DZMax Abort=0
UNET Convert EG Bridges=0
UNET Use Existing IB Tables=0
UNET Froude Limit=0
UNET Froude Power=0
Write IC File=0
Echo Input=False
Echo Output=False
Write Detailed=0

--- RotingCr.f01 (steady flow) ---

Flow Title=NFF Regression Equation
Program Version=4.00
Number of Profiles= 1
Profile Names=P100yr
River Rch & RM=RotingCr,Main            ,37619.8
1143.916
River Rch & RM=RotingCr,Main            ,34019.8
1302.469
River Rch & RM=RotingCr,Main            ,29219.8
 1435.42
River Rch & RM=RotingCr,Main            ,28819.8
1738.446
River Rch & RM=RotingCr,Main            ,26419.8
1819.489
River Rch & RM=RotingCr,Main            ,25785.4
1974.617
River Rch & RM=RotingCr,Main            ,22019.8
2130.023
River Rch & RM=RotingCr,Main            ,21619.8
2134.115
River Rch & RM=RotingCr,Main            ,16419.8
2295.587
River Rch & RM=RotingCr,Main            ,14057.8
2357.268
River Rch & RM=RotingCr,Main            ,13561.8
2627.604
River Rch & RM=RotingCr,Main            ,12019.8
2632.921
River Rch & RM=RotingCr,Main            ,8970.5
2648.829
River Rch & RM=RotingCr,Main            ,8351.1
2913.302
River Rch & RM=RotingCr,Main            ,2500.1
3215.112
River Rch & RM=RotingCr,Main            ,19.8
3244.379
River Rch & RM=RotingCr,Main            ,19.8
3247.449
Boundary for River Rch & Prof#=RotingCr,Main            , 1
Up Type= 0
Dn Type= 3
Dn Slope=0.001264
DSS Import GetInterval= 0
DSS Import GetPeak= 0
DSS Import FillOption= 0

--- RotingCr.g01 (geometry) ---

Geom Title=USGS 3m DEM
Program Version=4.00

River Reach=RotingCr     ,Main
Reach XY= 30
     1745390.446      220567.487     1745568.249      220808.843
     1745076.495      221674.141     1745470.406      221868.585
     1745151.207      222163.041     1745477.079      222143.014
     1746413.300      224177.533     1747556.381      224478.779
     1747904.214      225247.269     1747894.264      226090.136
     1746585.847      227455.544     1746919.664      227653.667
     1746893.177      228428.674     1746413.440      229835.898
     1746502.015      230257.618     1746756.661      230148.237
     1746958.327      231930.153     1748093.774      232952.042
     1747577.982      236703.622     1748019.784      236576.405
     1747849.670      237458.509     1748785.289      238320.497
     1748864.563      238803.233     1749119.813      238664.157
     1749377.571      239795.411     1751708.933      239947.844
     1751569.985      240294.571     1751846.964      240243.679
     1752913.490      241415.035     1752668.202      242253.258

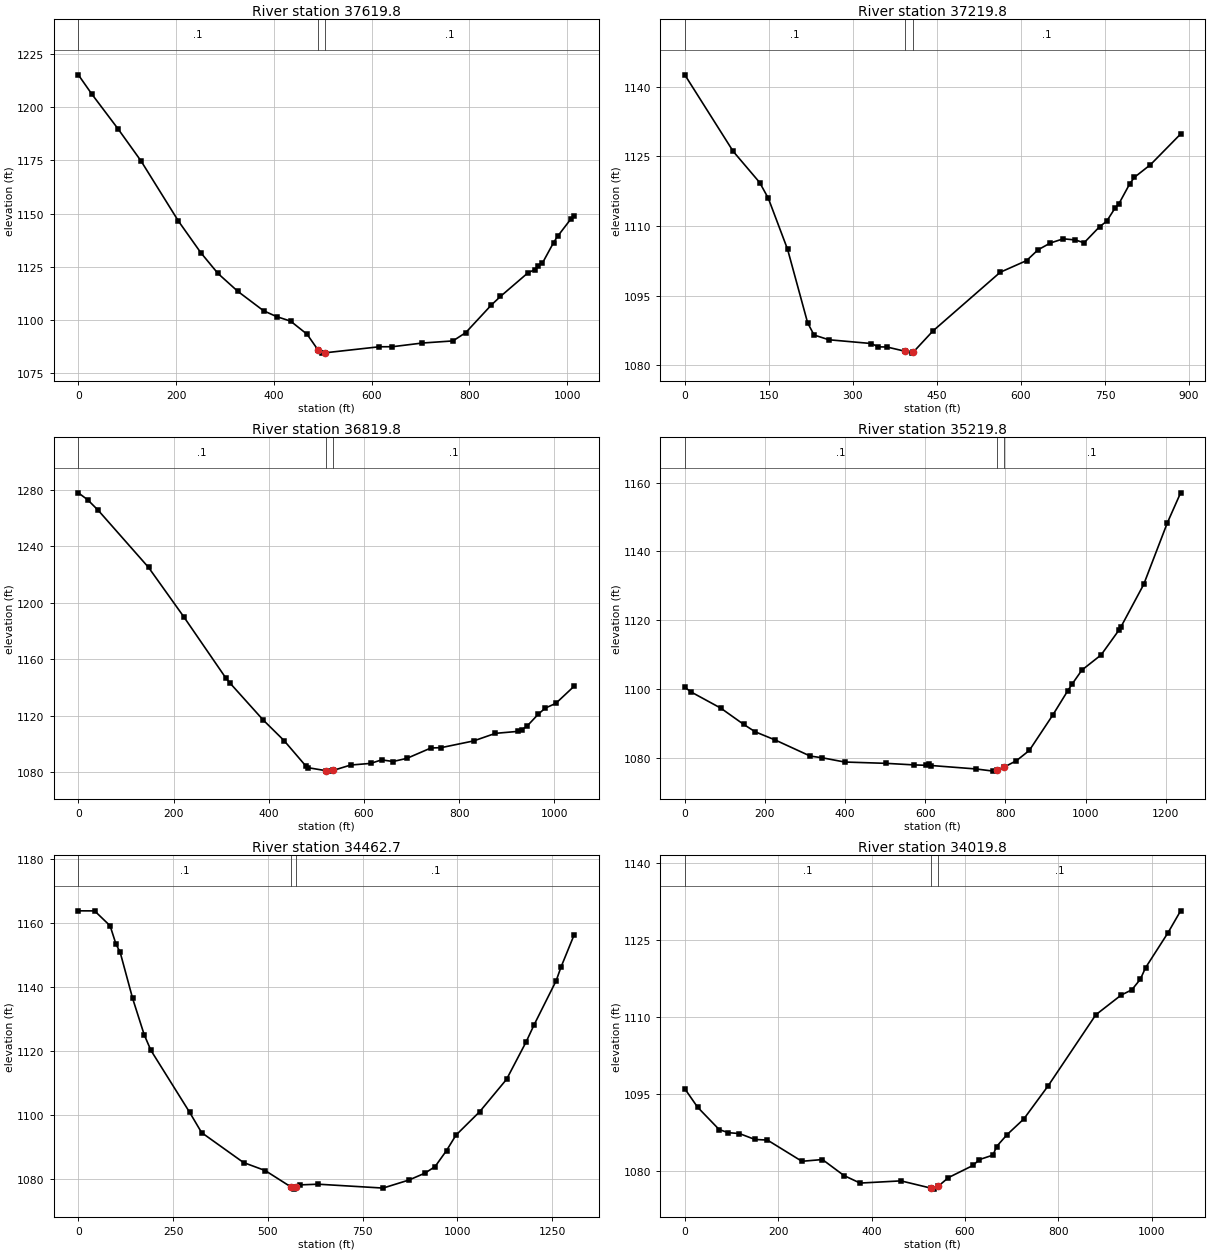
Type RM Length L Ch R = 1 ,37619.8,384.355,400,424.314
XS GIS Cut Line= 3
     1744906.569      220683.386     1745393.127      220577.036
     1745862.254      220361.420
#Sta/Elev= 30
       0 1215.22    27.6 1206.16    80.8 1189.96   127.9 1174.87   204.8 1146.47
   250.7 1131.59   285.6 1121.88   326.1 1113.50   378.8 1104.37   405.5 1101.61
   434.2 1099.48   468.0 1093.30   490.5 1085.87   499.3 1084.44   505.5 1084.61
   615.8 1087.43   642.4 1087.45   703.5 1089.18   766.3 1090.18   792.4 1094.05
   844.6 1106.98   863.5 1111.07   920.2 1122.26   934.2 1123.69   941.3 1125.57
   949.2 1126.68   972.2 1136.39   980.4 1139.33  1007.1 1147.33  1014.3 1149.06
#Mann= 3 , 0 , 0
       0     0.1       0   490.5   0.045       0   505.5     0.1       0
Bank Sta=   490.5,   505.5
Exp/Cntr=0.3,0.1

Type RM Length L Ch R = 1 ,37219.8,409.149,400,356.882
XS GIS Cut Line= 3
     1745152.325      220713.452     1745509.221      220894.674
     1745903.090      221177.001
#Sta/Elev= 30
       0 1142.59    86.3 1126.11   133.6 1119.39   149.1 1115.98   183.5 1104.97
   219.2 1089.17   230.6 1086.54   257.1 1085.51   332.6 1084.70   345.5 1083.98
   360.8 1083.95   392.8 1083.04   406.1 1082.63   407.8 1082.85   442.8 1087.40
   562.9 1100.05   610.0 1102.57   630.3 1104.88   652.5 1106.36   675.5 1107.26
   697.2 1107.01   712.6 1106.40   740.6 1109.91   752.7 1111.01   768.2 1113.94
   774.2 1114.69   794.0 1119.09   802.3 1120.50   831.1 1123.23   884.9 1129.84
#Mann= 3 , 0 , 0
       0     0.1       0   392.8   0.045       0   407.8     0.1       0
Bank Sta=   392.8,   407.8
Exp/Cntr=0.3,0.1

Type RM Length L Ch R = 1 ,36819.8,1597.064,1600,1283.007
XS GIS Cut Line= 3
     1744848.923      221088.131     1745372.929      221149.875
     1745874.167      221263.125
#Sta/Elev= 30
       0 1277.87    19.7 1272.92    41.8 1265.46   147.4 1225.04   221.4 1190.06
   309.9 1146.59   318.2 1143.18   388.5 1116.80   432.1 1102.30   478.7 1083.95
   482.5 1083.08   520.1 1080.96   526.1 1080.64   535.1 1081.13   572.0 1084.95
   614.0 1086.12   637.1 1088.62   661.0 1087.46   690.3 1089.71   740.7 1097.05
   761.7 1097.25   830.4 1102.05   876.0 1107.41   922.7 1108.79   932.1 1110.13
   942.5 1112.52   966.5 1121.11   980.8 1125.31  1003.0 1128.66  1041.5 1140.84
#Mann= 3 , 0 , 0
       0     0.1       0   520.1   0.045       0   535.1     0.1       0
Bank Sta=   520.1,   535.1
Exp/Cntr=0.3,0.1

Type RM Length L Ch R = 1 ,35219.8,763.17,757.136,731.331
XS GIS Cut Line= 3
     1744686.359      221946.156     1745470.348      221868.637
     1745917.710      221912.698
#Sta/Elev= 30
       0 1100.46    15.1 1099.12    89.8 1094.38   147.3 1089.62   175.7 1087.49
   225.4 1085.12   313.0 1080.43   342.7 1079.94   398.8 1078.70   503.2 1078.31
   571.8 1077.86   603.0 1077.74   609.1 1077.98   615.6 1077.68   726.7 1076.68
   769.8 1076.05   780.3 1076.49   795.3 1077.13   827.5 1079.08   859.7 1082.07
   917.9 1092.30   955.1 1099.33   966.2 1101.32   990.9 1105.45  1038.9 1109.87
  1084.3 1117.23  1088.7 1118.09  1145.1 1130.36  1204.2 1148.31  1237.3 1157.03
#Mann= 3 , 0 , 0
       0     0.1       0   780.3   0.045       0   795.3     0.1       0
Bank Sta=   780.3,   795.3
Exp/Cntr=0.3,0.1

Type RM Length L Ch R = 1 ,34462.7,447.506,442.865,456.955
XS GIS Cut Line= 3
     1744870.814      222619.236     1745293.080      222127.709
     1745927.597      221946.738
#Sta/Elev= 30
       0 1163.75    42.9 1163.73    83.8 1159.08    99.3 1153.35   110.3 1150.81
   143.2 1136.41   173.7 1125.07   191.3 1120.21   293.6 1100.83   325.2 1094.49
   435.7 1085.15   492.7 1082.66   560.2 1077.58   569.4 1076.85   575.2 1077.37
   584.1 1078.17   632.5 1078.39   803.7 1077.18   872.0 1079.69   914.6 1081.86
   941.0 1083.89   971.1 1088.89   996.1 1093.71  1058.7 1101.04  1129.5 1111.14
  1180.9 1122.77  1202.1 1128.15  1260.4 1141.94  1273.0 1146.15  1307.8 1156.27
#Mann= 3 , 0 , 0
       0     0.1       0   560.2   0.045       0   575.2     0.1       0
Bank Sta=   560.2,   575.2
Exp/Cntr=0.3,0.1

Type RM Length L Ch R = 1 ,34019.8,386.816,400,389.941
XS GIS Cut Line= 3
     1745103.174      222693.510     1745473.179      222306.602
     1745982.467      222171.997
#Sta/Elev= 30
       0 1095.97    27.3 1092.38    73.7 1088.00    93.3 1087.40   116.9 1087.23
   150.1 1086.08   177.0 1085.96   250.8 1081.82   294.8 1082.16   341.1 1079.03
   375.5 1077.57   463.0 1078.00   527.9 1076.57   534.5 1076.39   542.9 1076.96
   564.7 1078.64   617.1 1081.00   631.0 1082.15   660.2 1083.03   667.7 1084.69
   690.4 1087.03   726.1 1090.07   778.2 1096.53   880.3 1110.39   934.4 1114.22
   957.4 1115.26   975.6 1117.31   987.0 1119.59  1034.6 1126.34  1062.0 1130.67
#Mann= 3 , 0 , 0
       0     0.1       0   527.9   0.045       0   542.9     0.1       0
Bank Sta=   527.9,   542.9
Exp/Cntr=0.3,0.1

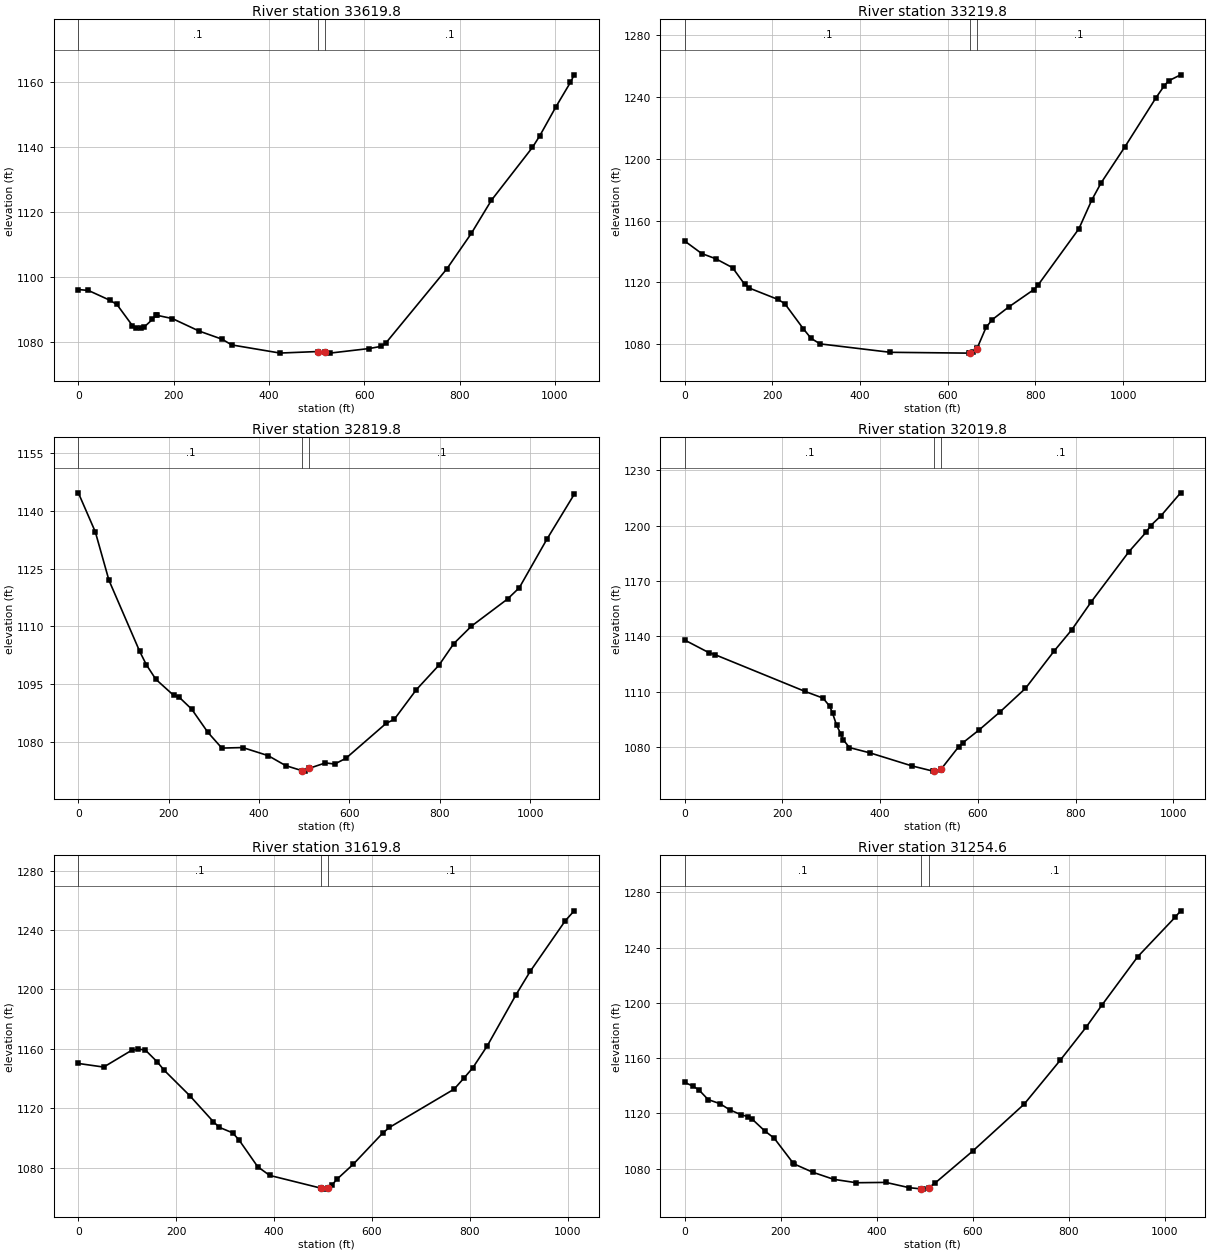
Type RM Length L Ch R = 1 ,33619.8,404.641,400,408.561
XS GIS Cut Line= 3
     1745160.272      222796.714     1745650.128      222656.693
     1746070.549      222332.104
#Sta/Elev= 30
       0 1096.03    21.1 1095.75    65.8 1092.76    81.0 1091.43   113.4 1084.94
   121.1 1084.20   130.6 1084.09   137.5 1084.40   155.5 1086.83   162.2 1088.07
   164.4 1088.12   197.3 1087.10   253.5 1083.25   301.9 1080.73   321.8 1078.99
   423.3 1076.48     502 1076.95     517 1076.72   527.7 1076.46   610.7 1077.88
   636.1 1078.56   644.7 1079.45   773.9 1102.49   824.7 1113.29   867.0 1123.52
   953.1 1139.78   968.5 1143.36  1001.6 1152.08  1032.9 1159.82  1040.6 1162.11
#Mann= 3 , 0 , 0
       0     0.1       0     502   0.045       0     517     0.1       0
Bank Sta=     502,     517
Exp/Cntr=0.3,0.1

Type RM Length L Ch R = 1 ,33219.8,390.446,400,404.62
XS GIS Cut Line= 3
     1745302.167      223120.361     1745889.576      222823.060
     1746340.237      222680.040
#Sta/Elev= 30
       0 1146.69    38.5 1138.69    70.7 1135.30   109.0 1129.54   136.5 1118.81
   147.5 1116.34   211.6 1109.15   227.9 1106.41   270.3 1090.15   288.0 1083.94
   308.6 1080.35   468.7 1074.91   648.1 1074.38   650.9 1074.39   658.4 1074.86
   665.9 1077.31   667.2 1077.73   687.5 1091.12   701.6 1096.03   738.7 1104.11
   796.4 1115.42   805.3 1118.08   899.1 1154.66   928.8 1173.41   949.8 1184.31
  1003.5 1207.31  1075.1 1239.30  1094.1 1247.09  1103.7 1250.16  1131.2 1254.05
#Mann= 3 , 0 , 0
       0     0.1       0   650.9   0.045       0   665.9     0.1       0
Bank Sta=   650.9,   665.9
Exp/Cntr=0.3,0.1

Type RM Length L Ch R = 1 ,32819.8,809.584,800,795.253
XS GIS Cut Line= 3
     1745319.973      223207.029     1745821.051      223158.240
     1746410.338      223082.922
#Sta/Elev= 30
       0 1144.66    37.6 1134.52    67.8 1121.95   135.9 1103.48   150.8 1099.99
   171.5 1096.26   210.7 1092.12   222.5 1091.69   250.8 1088.52   286.9 1082.46
   317.7 1078.40   363.9 1078.54   420.2 1076.44   458.8 1073.86   495.9 1072.51
   501.0 1072.42   510.9 1073.14   547.0 1074.56   567.3 1074.25   592.3 1075.75
   681.4 1084.83   699.2 1085.85   748.1 1093.55   798.5 1099.96   831.2 1105.54
   870.2 1110.06   950.1 1117.10   976.0 1120.01  1037.1 1132.61  1097.5 1144.25
#Mann= 3 , 0 , 0
       0     0.1       0   495.9   0.045       0   510.9     0.1       0
Bank Sta=   495.9,   510.9
Exp/Cntr=0.3,0.1

Type RM Length L Ch R = 1 ,32019.8,400.11,400,394.013
XS GIS Cut Line= 3
     1745715.144      223965.334     1746158.389      223697.762
     1746623.909      223522.394
#Sta/Elev= 30
       0 1138.04    50.0 1131.14    62.0 1130.14   246.5 1110.24   283.0 1106.66
   296.8 1102.22   302.5 1098.54   310.7 1092.03   319.8 1087.03   324.6 1084.07
   337.1 1079.89   379.5 1077.00   464.6 1070.01   508.1 1067.15   510.2 1067.25
   524.1 1068.00   525.2 1068.37   560.5 1080.27   569.4 1082.51   602.7 1089.45
   645.5 1099.21   697.5 1111.92   756.8 1132.32   791.9 1143.47   832.1 1158.72
   909.6 1185.95   944.1 1196.26   953.8 1199.95   975.1 1205.33  1015.2 1217.71
#Mann= 3 , 0 , 0
       0     0.1       0   510.2   0.045       0   525.2     0.1       0
Bank Sta=   510.2,   525.2
Exp/Cntr=0.3,0.1

Type RM Length L Ch R = 1 ,31619.8,371.613,365.169,360.109
XS GIS Cut Line= 3
     1745912.313      224304.222     1746340.699      224039.949
     1746754.407      223741.881
#Sta/Elev= 30
       0 1150.14    51.8 1147.71   108.8 1158.96   122.7 1159.78   136.7 1159.23
   161.0 1151.29   175.5 1145.55   227.7 1128.45   275.9 1110.93   288.0 1107.14
   315.2 1103.45   328.3 1098.66   366.5 1080.62   390.9 1074.77   495.8 1066.17
   504.9 1065.52   510.8 1066.48   518.0 1068.26   529.3 1072.42   561.5 1082.18
   622.1 1103.30   635.8 1107.09   767.9 1132.85   788.9 1140.63   805.9 1147.14
   835.7 1162.02   894.5 1196.49   923.5 1212.23   995.0 1246.21  1013.2 1252.92
#Mann= 3 , 0 , 0
       0     0.1       0   495.8   0.045       0   510.8     0.1       0
Bank Sta=   495.8,   510.8
Exp/Cntr=0.3,0.1

Type RM Length L Ch R = 1 ,31254.6,445.117,434.831,417.223
XS GIS Cut Line= 3
     1746278.478      224636.992     1746612.262      224235.827
     1746859.304      223787.881
#Sta/Elev= 30
       0 1142.41    17.7 1139.51    29.3 1137.00    48.6 1129.96    73.4 1126.96
    93.6 1122.54   117.8 1118.89   131.6 1117.64   139.3 1116.15   166.2 1107.39
   186.4 1101.96   225.0 1084.34   228.5 1083.23   266.2 1077.40   310.2 1072.22
   357.5 1069.74   419.1 1069.98   467.6 1066.16   493.2 1065.25   497.4 1065.11
   508.2 1066.14   521.9 1069.58   600.4 1092.77   707.2 1126.61   782.2 1158.32
   836.3 1182.31   868.8 1198.09   944.0 1233.41  1021.7 1261.89  1033.4 1266.62
#Mann= 3 , 0 , 0
       0     0.1       0   493.2   0.045       0   508.2     0.1       0
Bank Sta=   493.2,   508.2
Exp/Cntr=0.3,0.1

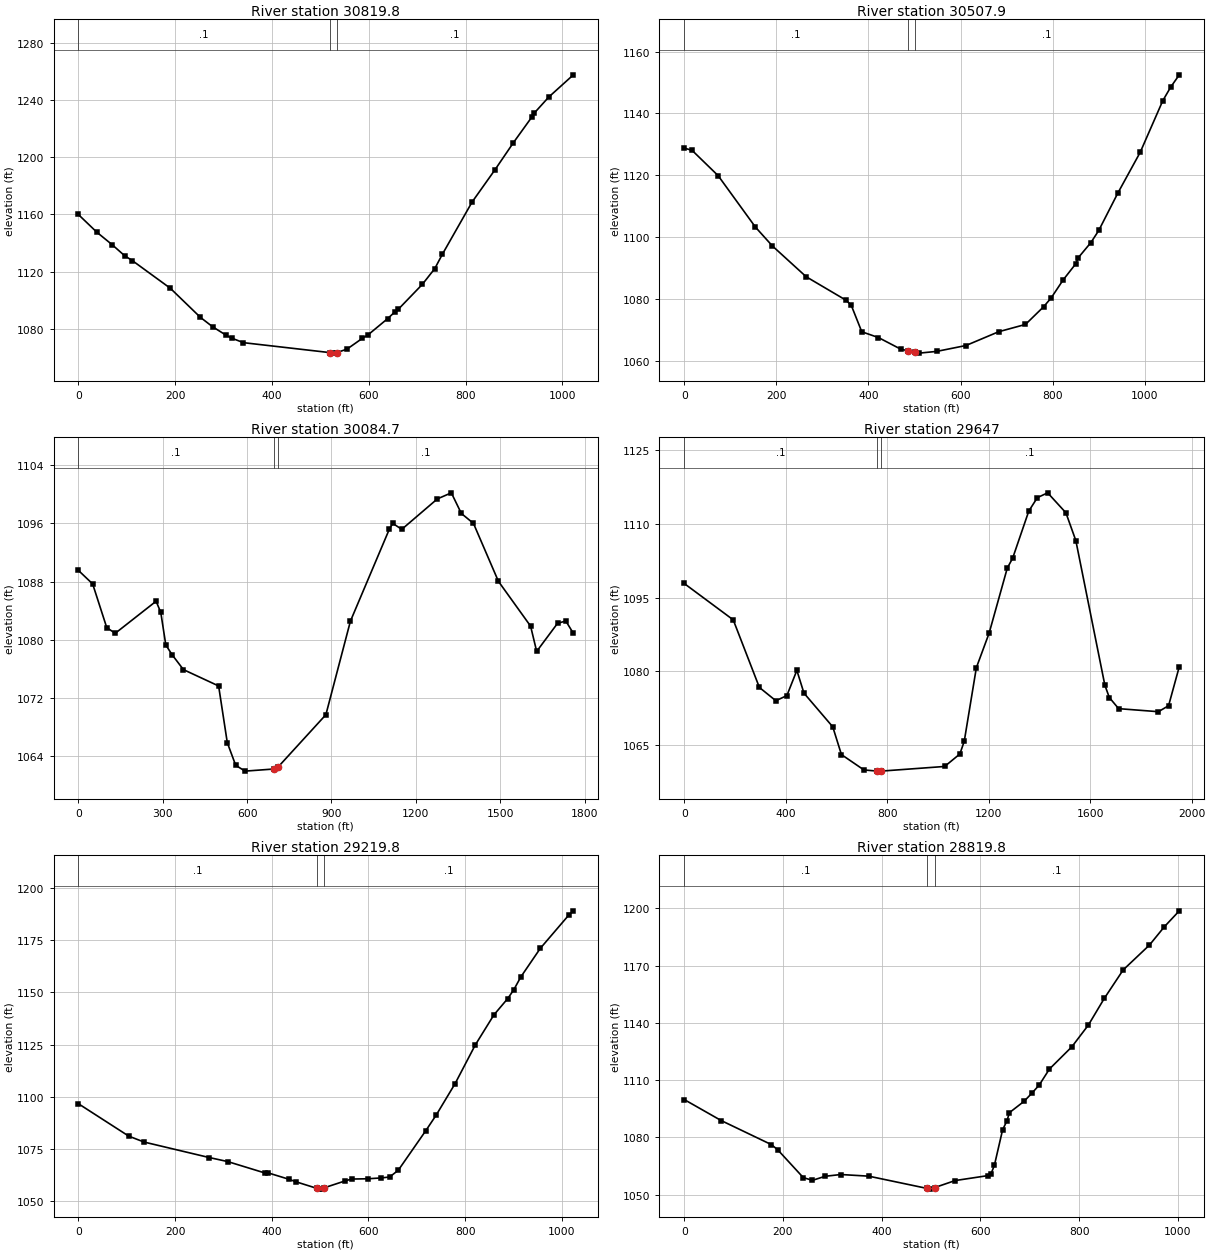
Type RM Length L Ch R = 1 ,30819.8,307.672,311.936,316.067
XS GIS Cut Line= 3
     1746806.998      224855.225     1746969.004      224354.011
     1746971.610      223857.993
#Sta/Elev= 30
       0 1159.92    38.3 1147.52    69.8 1138.83    95.7 1131.11   111.6 1127.69
   190.1 1108.37   252.4 1088.01   277.8 1081.41   306.1 1075.41   317.2 1073.49
   341.1 1070.37   519.2 1063.45   530.5 1063.06   534.2 1063.47   555.1 1065.85
   587.1 1073.46   598.8 1075.87   639.0 1087.13   654.5 1091.99   661.1 1093.69
   710.7 1111.06   736.5 1122.12   751.9 1131.96   813.5 1168.57   860.8 1191.11
   899.1 1210.15   936.6 1227.77   941.4 1230.50   972.1 1241.97  1022.8 1257.44
#Mann= 3 , 0 , 0
       0     0.1       0   519.2   0.045       0   534.2     0.1       0
Bank Sta=   519.2,   534.2
Exp/Cntr=0.3,0.1

Type RM Length L Ch R = 1 ,30507.9,419.668,423.213,434.236
XS GIS Cut Line= 3
     1746961.382      224948.454     1747207.806      224517.377
     1747304.498      223947.404
#Sta/Elev= 30
       0 1128.82    17.0 1128.10    73.6 1119.92   154.6 1103.30   191.3 1097.23
   264.8 1087.27   351.5 1079.67   362.7 1078.01   385.4 1069.51   421.7 1067.63
   470.2 1063.88     485 1063.40     500 1062.92   510.1 1062.61   548.0 1063.17
   611.6 1065.07   682.6 1069.52   740.8 1071.88   779.9 1077.55   796.4 1080.41
   822.6 1086.26   850.3 1091.53   854.9 1093.34   882.8 1098.32   899.8 1102.21
   941.1 1114.25   989.8 1127.46  1038.8 1144.12  1056.2 1148.57  1074.7 1152.48
#Mann= 3 , 0 , 0
       0     0.1       0     485   0.045       0     500     0.1       0
Bank Sta=     485,     500
Exp/Cntr=0.3,0.1

Type RM Length L Ch R = 1 ,30084.7,428.592,437.629,445.775
XS GIS Cut Line= 3
     1747159.092      225057.451     1747680.274      224286.168
     1748123.506      223585.295
#Sta/Elev= 30
       0 1089.55    51.1 1087.67   101.1 1081.66   131.2 1080.87   276.6 1085.29
   293.3 1083.74   311.1 1079.27   333.5 1077.92   373.8 1075.87   498.9 1073.62
   529.7 1065.81   559.6 1062.69   593.0 1061.89   694.4 1062.18   709.4 1062.42
   880.2 1069.66   967.4 1082.54  1106.0 1095.23  1118.1 1096.01  1150.0 1095.19
  1276.4 1099.38  1326.2 1100.22  1361.8 1097.38  1404.9 1096.01  1493.6 1088.03
  1608.0 1081.86  1629.6 1078.38  1703.7 1082.24  1733.2 1082.57  1760.1 1080.86
#Mann= 3 , 0 , 0
       0     0.1       0   694.4   0.045       0   709.4     0.1       0
Bank Sta=   694.4,   709.4
Exp/Cntr=0.3,0.1

Type RM Length L Ch R = 1 ,29647,424.119,427.222,416.654
XS GIS Cut Line= 3
     1747067.046      225179.645     1747724.042      224778.271
     1748797.454      224284.882
#Sta/Elev= 30
       0 1097.91   193.1 1090.51   296.2 1076.75   361.1 1074.04   404.6 1075.09
   443.9 1080.22   471.9 1075.59   585.4 1068.73   619.6 1063.08   708.3 1059.95
   760.1 1059.72   775.1 1059.71  1026.4 1060.66  1086.4 1063.20  1103.7 1065.80
  1151.4 1080.77  1201.8 1087.82  1273.4 1101.07  1294.3 1103.04  1358.1 1112.66
  1391.8 1115.39  1432.4 1116.37  1504.3 1112.31  1543.5 1106.64  1657.8 1077.22
  1675.4 1074.70  1712.1 1072.43  1868.8 1071.81  1909.0 1073.03  1951.3 1081.00
#Mann= 3 , 0 , 0
       0     0.1       0   760.1   0.045       0   775.1     0.1       0
Bank Sta=   760.1,   775.1
Exp/Cntr=0.3,0.1

Type RM Length L Ch R = 1 ,29219.8,391.77,400,401.854
XS GIS Cut Line= 3
     1747353.922      225214.156     1747834.988      225072.282
     1748352.220      225001.190
#Sta/Elev= 30
       0 1096.72   104.3 1081.16   136.0 1078.32   271.0 1070.88   308.5 1068.99
   385.4 1063.53   392.8 1063.52   435.9 1060.46   449.6 1059.31     494 1056.08
   497.5 1055.81   500.2 1055.76     509 1056.44   550.7 1059.63   565.2 1060.59
   599.4 1060.73   625.9 1061.12   643.6 1061.57   661.5 1064.78   718.6 1083.82
   739.9 1091.21   779.1 1106.34   820.8 1124.85   859.3 1139.26   887.9 1147.08
   900.3 1151.26   915.0 1157.46   955.2 1171.13  1014.3 1187.13  1023.6 1189.12
#Mann= 3 , 0 , 0
       0     0.1       0     494   0.045       0     509     0.1       0
Bank Sta=     494,     509
Exp/Cntr=0.3,0.1

Type RM Length L Ch R = 1 ,28819.8,399.575,400,402.955
XS GIS Cut Line= 3
     1747407.247      225447.501     1747907.302      225454.982
     1748408.769      225419.735
#Sta/Elev= 30
       0 1099.84    74.7 1088.86   176.7 1076.22   189.6 1073.47   241.2 1058.95
   259.8 1057.54   285.4 1059.66   317.3 1060.58   373.7 1059.72   492.6 1053.26
   498.7 1052.93   507.6 1053.77   548.6 1057.41   616.3 1060.05   621.6 1061.10
   628.2 1065.35   644.9 1084.04   653.7 1088.67   658.6 1092.96   688.5 1098.94
   704.6 1103.29   719.0 1107.42   739.7 1115.81   785.1 1127.45   818.7 1138.88
   850.8 1152.79   889.1 1167.72   942.2 1180.70   972.4 1190.29  1002.8 1198.66
#Mann= 3 , 0 , 0
       0     0.1       0   492.6   0.045       0   507.6     0.1       0
Bank Sta=   492.6,   507.6
Exp/Cntr=0.3,0.1

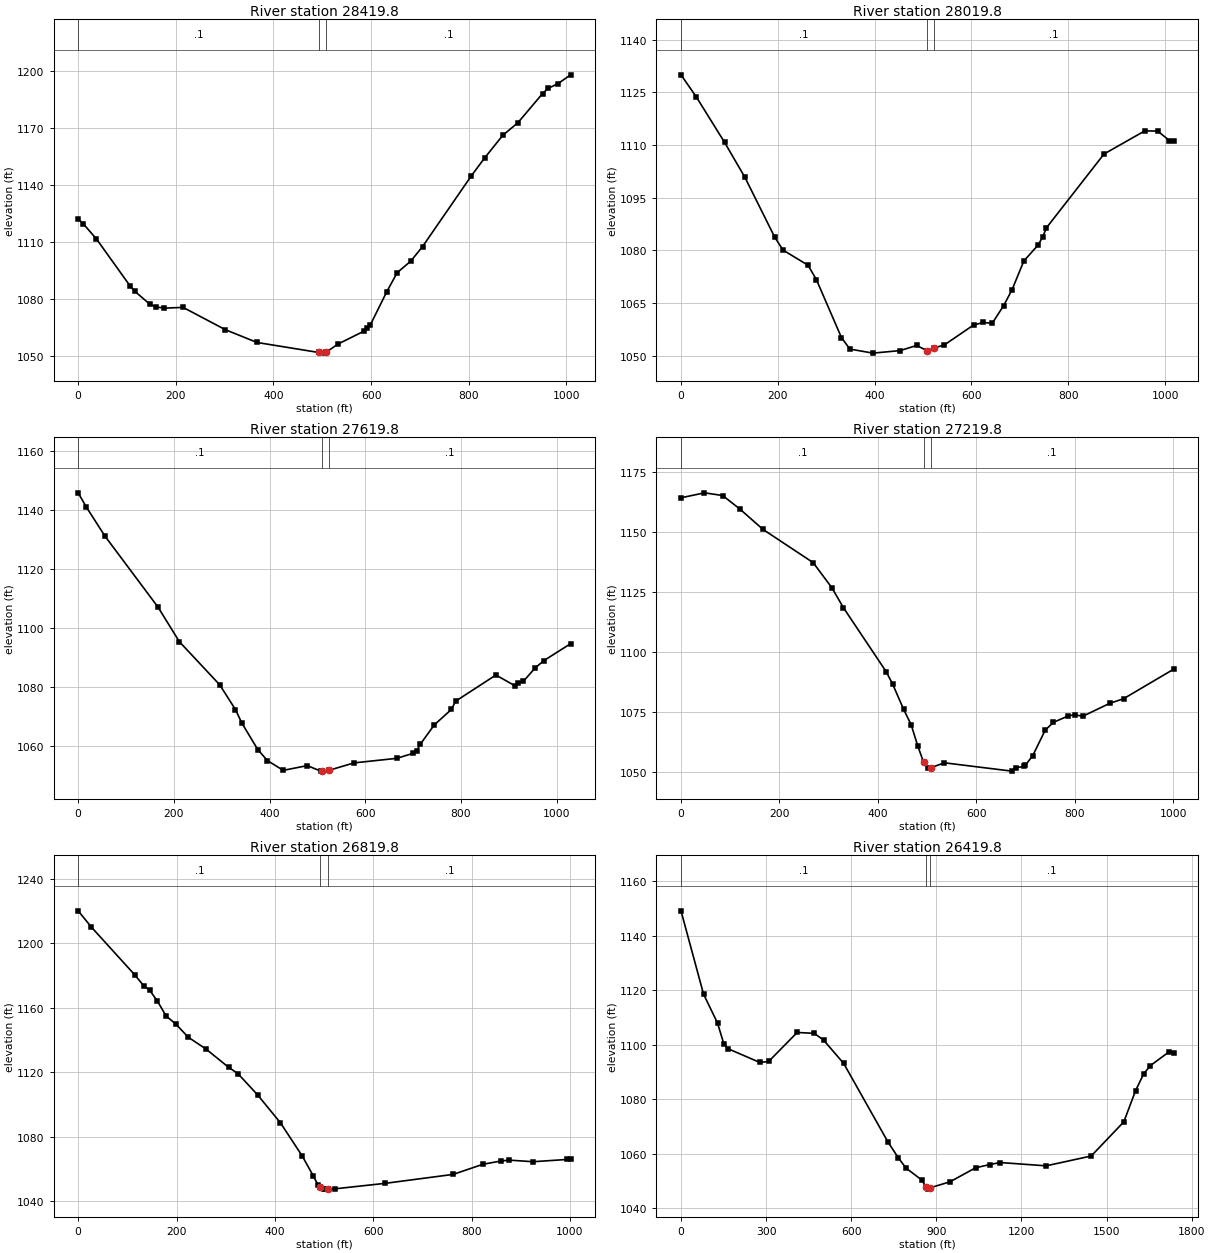
Type RM Length L Ch R = 1 ,28419.8,388.731,400,413.041
XS GIS Cut Line= 3
     1747390.143      225827.794     1747890.005      225844.842
     1748397.649      225875.803
#Sta/Elev= 30
       0 1122.06    10.1 1119.65    37.3 1111.60   107.1 1086.51   116.0 1083.97
   147.2 1077.06   159.4 1075.77   175.8 1075.08   214.9 1075.48   301.4 1063.73
   366.2 1056.99   492.7 1051.71   505.3 1051.37   507.7 1051.84   532.8 1056.24
   586.0 1063.03   591.4 1064.77   597.9 1065.99   632.2 1083.82   653.4 1093.80
   681.2 1099.86   705.4 1107.56   805.5 1144.91   832.3 1154.20   869.8 1166.21
   900.5 1172.79   951.2 1188.20   962.2 1190.87   982.5 1193.39  1008.7 1198.06
#Mann= 3 , 0 , 0
       0     0.1       0   492.7   0.045       0   507.7     0.1       0
Bank Sta=   492.7,   507.7
Exp/Cntr=0.3,0.1

Type RM Length L Ch R = 1 ,28019.8,389.708,400,410.006
XS GIS Cut Line= 3
     1747359.728      225934.815     1747799.099      226205.581
     1748199.736      226507.038
#Sta/Elev= 30
       0 1129.97    31.6 1123.69    89.9 1110.77   132.2 1100.74   193.5 1083.76
   210.7 1080.06   262.5 1075.73   279.8 1071.62   331.5 1055.14   348.8 1051.86
   396.6 1050.70   452.6 1051.42   486.9 1052.88   508.6 1051.39   523.6 1052.19
   544.0 1053.03   604.5 1058.71   624.9 1059.45   642.9 1059.18   666.4 1064.19
   683.9 1068.74   708.3 1076.94   737.7 1081.47   747.4 1083.82   754.8 1086.36
   873.9 1107.41   958.4 1114.02   984.8 1113.93  1009.1 1111.26  1017.5 1111.12
#Mann= 3 , 0 , 0
       0     0.1       0   508.6   0.045       0   523.6     0.1       0
Bank Sta=   508.6,   523.6
Exp/Cntr=0.3,0.1

Type RM Length L Ch R = 1 ,27619.8,408.821,400,389.082
XS GIS Cut Line= 3
     1747279.769      226018.675     1747541.364      226463.644
     1747768.927      226923.678
#Sta/Elev= 30
       0 1145.93    17.2 1141.08    55.9 1131.28   166.9 1107.18   211.5 1095.47
   295.8 1080.86   328.8 1072.45   342.0 1067.91   375.6 1058.85   395.5 1055.18
   428.6 1051.85   478.9 1053.46   507.0 1051.59   508.7 1051.61   523.7 1051.84
   576.5 1054.38   666.1 1055.93   698.9 1057.57   707.4 1058.46   714.8 1060.63
   744.2 1067.24   780.1 1072.50   789.0 1075.31   873.1 1084.17   913.5 1080.47
   920.1 1081.48   930.7 1082.07   955.6 1086.64   973.3 1089.04  1029.4 1094.82
#Mann= 3 , 0 , 0
       0     0.1       0   508.7   0.045       0   523.7     0.1       0
Bank Sta=   508.7,   523.7
Exp/Cntr=0.3,0.1

Type RM Length L Ch R = 1 ,27219.8,402.999,400,398.229
XS GIS Cut Line= 3
     1746859.285      226440.829     1747267.021      226731.089
     1747674.758      227021.350
#Sta/Elev= 30
       0 1164.31    47.7 1166.39    84.7 1165.26   119.5 1159.65   166.6 1151.13
   268.6 1137.26   306.6 1126.78   329.9 1118.52   416.8 1091.80   429.9 1086.67
   452.3 1076.10   467.8 1069.58   481.5 1060.54     493 1053.98   501.9 1051.43
     508 1051.70   535.5 1053.71   672.2 1050.24   680.6 1051.72   697.7 1052.18
   700.1 1052.73   714.9 1056.75   740.3 1067.38   756.9 1070.60   787.5 1073.33
   799.9 1073.72   816.9 1073.17   871.1 1078.52   899.3 1080.45  1000.9 1092.74
#Mann= 3 , 0 , 0
       0     0.1       0     493   0.045       0     508     0.1       0
Bank Sta=     493,     508
Exp/Cntr=0.3,0.1

Type RM Length L Ch R = 1 ,26819.8,400.008,400,384.132
XS GIS Cut Line= 3
     1746571.992      226805.032     1747014.520      227038.505
     1747444.574      227296.304
#Sta/Elev= 30
       0 1220.19    27.1 1210.02   114.6 1180.62   133.8 1173.52   145.3 1170.94
   160.9 1164.30   179.0 1154.86   198.7 1149.92   223.9 1141.74   259.7 1134.49
   305.9 1123.09   325.0 1119.13   364.8 1106.02   411.5 1088.60   456.0 1067.89
   478.0 1055.81   487.5 1050.22   492.8 1048.75   500.3 1047.54   503.0 1047.48
   507.8 1047.53   522.9 1047.69   624.4 1051.07   762.8 1056.63   823.0 1062.89
   859.9 1064.93   875.8 1065.49   925.3 1064.49   994.7 1065.90  1001.7 1066.38
#Mann= 3 , 0 , 0
       0     0.1       0   492.8   0.045       0   507.8     0.1       0
Bank Sta=   492.8,   507.8
Exp/Cntr=0.3,0.1

Type RM Length L Ch R = 1 ,26419.8,647.665,634.412,625.386
XS GIS Cut Line= 3
     1746002.768      226918.406     1746762.583      227344.338
     1747623.365      227429.498
#Sta/Elev= 30
       0 1149.05    79.4 1118.53   128.7 1107.90   150.8 1100.34   165.0 1098.51
   278.0 1093.43   308.9 1093.79   409.5 1104.43   469.8 1104.11   502.4 1101.65
   573.4 1093.09   729.4 1064.29   766.4 1058.41   792.9 1054.72   847.8 1050.38
   863.6 1047.84   869.0 1046.97   878.6 1047.46   948.4 1049.67  1038.5 1054.80
  1087.8 1055.97  1124.8 1056.73  1287.0 1055.51  1445.9 1059.12  1560.9 1071.65
  1602.5 1083.14  1630.7 1089.20  1654.1 1092.25  1721.7 1097.42  1736.0 1096.82
#Mann= 3 , 0 , 0
       0     0.1       0   863.6   0.045       0   878.6     0.1       0
Bank Sta=   863.6,   878.6
Exp/Cntr=0.3,0.1

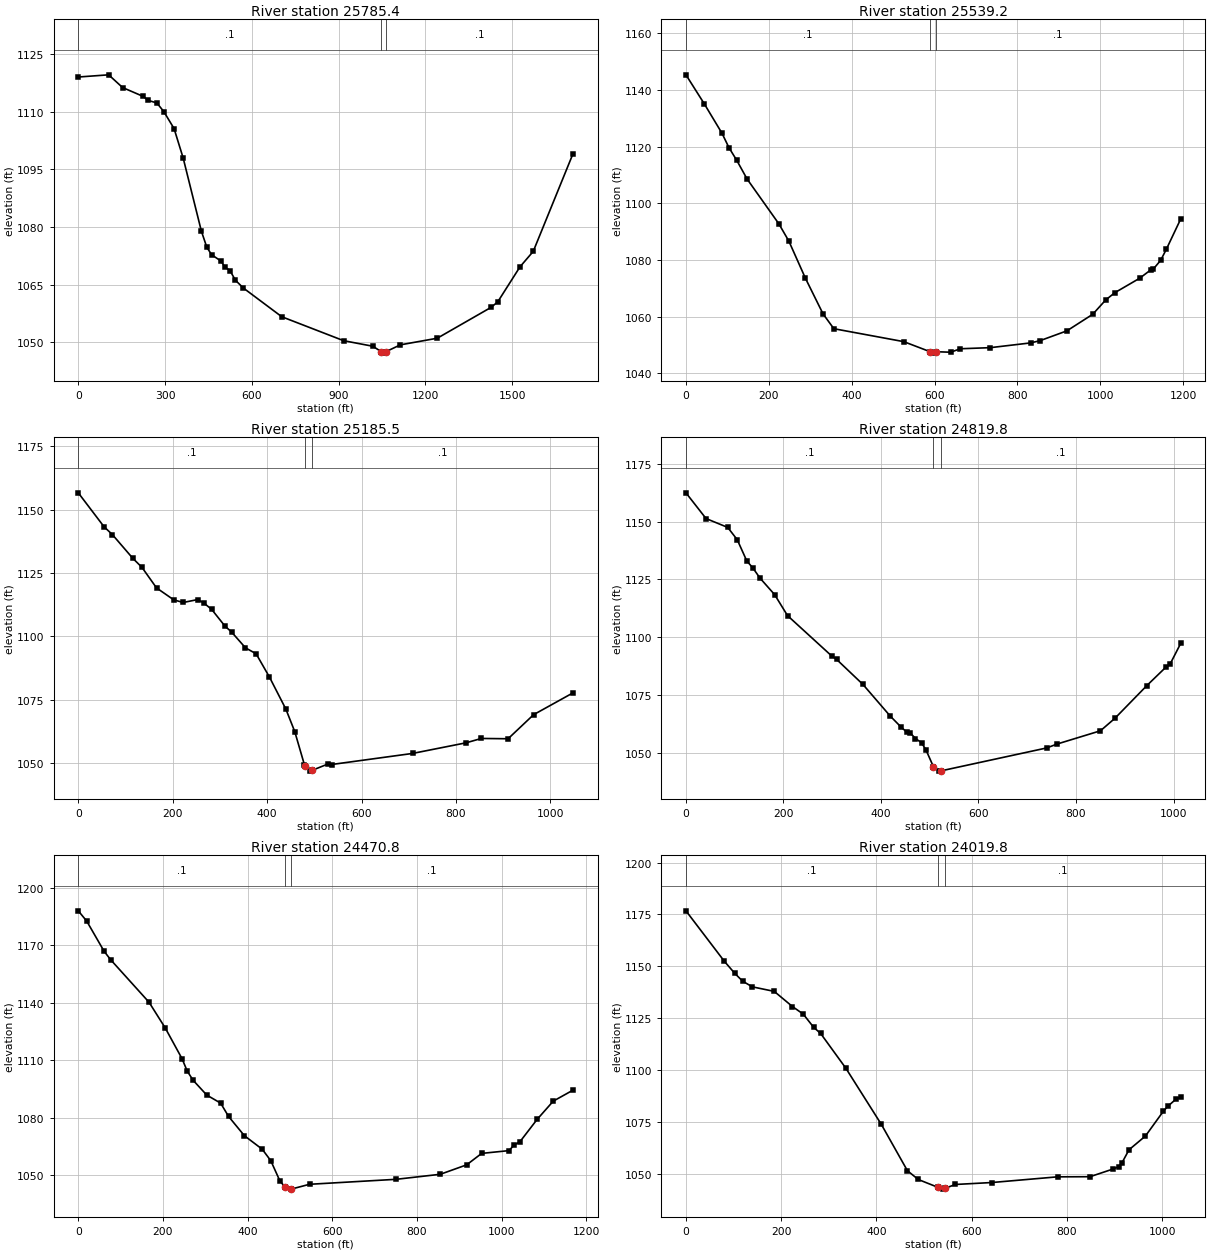
Type RM Length L Ch R = 1 ,25785.4,248.591,246.213,253.504
XS GIS Cut Line= 3
     1745863.583      227676.597     1746924.152      227670.110
     1747566.520      227572.066
#Sta/Elev= 30
       0 1119.04   105.0 1119.61   153.2 1116.30   225.0 1113.97   240.4 1112.98
   271.6 1112.29   295.6 1110.05   331.2 1105.61   362.8 1097.90   425.6 1078.90
   444.4 1074.71   461.0 1072.78   493.7 1071.09   507.1 1069.52   524.4 1068.66
   543.0 1066.15   570.7 1064.10   703.6 1056.62   917.3 1050.39  1018.5 1048.94
  1048.1 1047.49  1055.5 1047.15  1063.1 1047.51  1113.6 1049.31  1241.1 1051.03
  1427.0 1059.06  1450.0 1060.48  1527.1 1069.62  1572.9 1073.64  1710.4 1099.08
#Mann= 3 , 0 , 0
       0     0.1       0  1048.1   0.045       0  1063.1     0.1       0
Bank Sta=  1048.1,  1063.1
Exp/Cntr=0.3,0.1

Type RM Length L Ch R = 1 ,25539.2,359.941,353.681,346.286
XS GIS Cut Line= 3
     1746294.550      228013.191     1746875.486      227910.826
     1747466.970      228032.736
#Sta/Elev= 30
       0 1145.30    44.2 1135.09    87.1 1124.67   103.7 1119.65   122.6 1115.15
   147.6 1108.55   224.3 1092.75   248.4 1086.65   288.2 1073.61   330.8 1061.02
   356.9 1055.79   525.6 1051.23   587.9 1047.75   596.3 1047.18   602.9 1047.68
   638.8 1047.50   662.0 1048.72   734.6 1049.11   832.0 1050.79   854.6 1051.58
   919.3 1055.04   981.6 1060.88  1012.9 1065.93  1034.9 1068.49  1094.7 1073.57
  1121.9 1076.56  1128.0 1076.86  1145.5 1079.90  1159.1 1083.76  1193.8 1094.46
#Mann= 3 , 0 , 0
       0     0.1       0   587.9   0.045       0   602.9     0.1       0
Bank Sta=   587.9,   602.9
Exp/Cntr=0.3,0.1

Type RM Length L Ch R = 1 ,25185.5,355.149,365.695,373.513
XS GIS Cut Line= 3
     1746338.331      228411.436     1746797.342      228238.676
     1747353.042      228197.156
#Sta/Elev= 30
       0 1156.61    54.6 1143.23    72.1 1140.17   115.4 1130.81   134.8 1127.24
   165.7 1119.13   202.5 1114.38   222.4 1113.39   252.6 1114.52   265.3 1113.27
   282.5 1110.65   310.5 1104.10   324.8 1101.70   354.1 1095.50   376.6 1093.16
   404.9 1083.96   439.7 1071.31   458.5 1062.45   479.0 1049.33   480.5 1048.99
   490.4 1046.90   495.5 1047.23   529.2 1049.75   536.4 1049.51   707.8 1053.87
   821.4 1058.07   853.6 1059.78   910.2 1059.66   964.2 1069.15  1047.7 1077.76
#Mann= 3 , 0 , 0
       0     0.1       0   480.5   0.045       0   495.5     0.1       0
Bank Sta=   480.5,   495.5
Exp/Cntr=0.3,0.1

Type RM Length L Ch R = 1 ,24819.8,339.238,348.986,348.034
XS GIS Cut Line= 3
     1746332.002      228513.555     1746843.940      228570.334
     1747327.646      228695.431
#Sta/Elev= 30
       0 1162.45    41.2 1151.33    85.7 1147.49   105.2 1142.18   124.8 1132.99
   137.5 1129.90   151.9 1125.57   181.9 1118.43   208.4 1109.34   298.6 1091.97
   308.8 1090.46   363.1 1079.58   418.9 1065.94   441.2 1061.16   452.4 1059.07
   459.3 1058.79   470.8 1056.21   483.2 1054.38   492.3 1051.29   507.6 1044.01
   519.1 1042.11   522.6 1042.20   740.2 1052.15   761.1 1053.82   850.2 1059.56
   880.0 1064.99   945.4 1079.12   985.1 1087.21   992.7 1088.28  1014.7 1097.33
#Mann= 3 , 0 , 0
       0     0.1       0   507.6   0.045       0   522.6     0.1       0
Bank Sta=   507.6,   522.6
Exp/Cntr=0.3,0.1

Type RM Length L Ch R = 1 ,24470.8,449.43,451.014,447.525
XS GIS Cut Line= 3
     1746319.762      228632.115     1746743.384      228891.744
     1747384.304      229091.753
#Sta/Elev= 30
       0 1187.89    19.9 1182.54    60.9 1166.85    76.3 1162.45   167.1 1140.26
   205.3 1126.88   245.1 1110.81   257.3 1104.37   271.2 1099.59   303.4 1091.89
   336.2 1087.69   354.8 1080.78   392.3 1070.71   434.3 1063.69   454.6 1057.70
   476.0 1047.21   488.3 1043.92   502.7 1042.88   503.3 1042.92   546.1 1045.40
   750.9 1048.00   855.0 1050.62   917.2 1055.54   952.6 1061.50  1017.0 1062.94
  1029.1 1065.83  1042.9 1067.55  1083.6 1079.23  1121.6 1088.72  1168.3 1094.46
#Mann= 3 , 0 , 0
       0     0.1       0   488.3   0.045       0   503.3     0.1       0
Bank Sta=   488.3,   503.3
Exp/Cntr=0.3,0.1

Type RM Length L Ch R = 1 ,24019.8,441.078,432.081,434.448
XS GIS Cut Line= 3
     1746167.913      229090.007     1746664.884      229293.025
     1747166.652      229296.742
#Sta/Elev= 30
       0 1176.74    80.4 1152.52   102.1 1146.74   118.9 1142.91   139.2 1140.16
   185.3 1137.97   223.6 1130.67   246.3 1127.02   268.0 1120.70   282.8 1117.70
   335.7 1100.98   410.2 1073.95   464.9 1051.67   487.7 1047.43   529.3 1043.63
   539.6 1042.79   544.3 1043.19   565.4 1045.03   641.7 1045.96   780.3 1048.71
   848.3 1048.77   897.2 1052.51   909.4 1053.68   915.5 1055.52   930.1 1061.72
   964.7 1068.37  1002.4 1080.33  1012.0 1082.75  1028.5 1086.06  1038.6 1087.12
#Mann= 3 , 0 , 0
       0     0.1       0   529.3   0.045       0   544.3     0.1       0
Bank Sta=   529.3,   544.3
Exp/Cntr=0.3,0.1