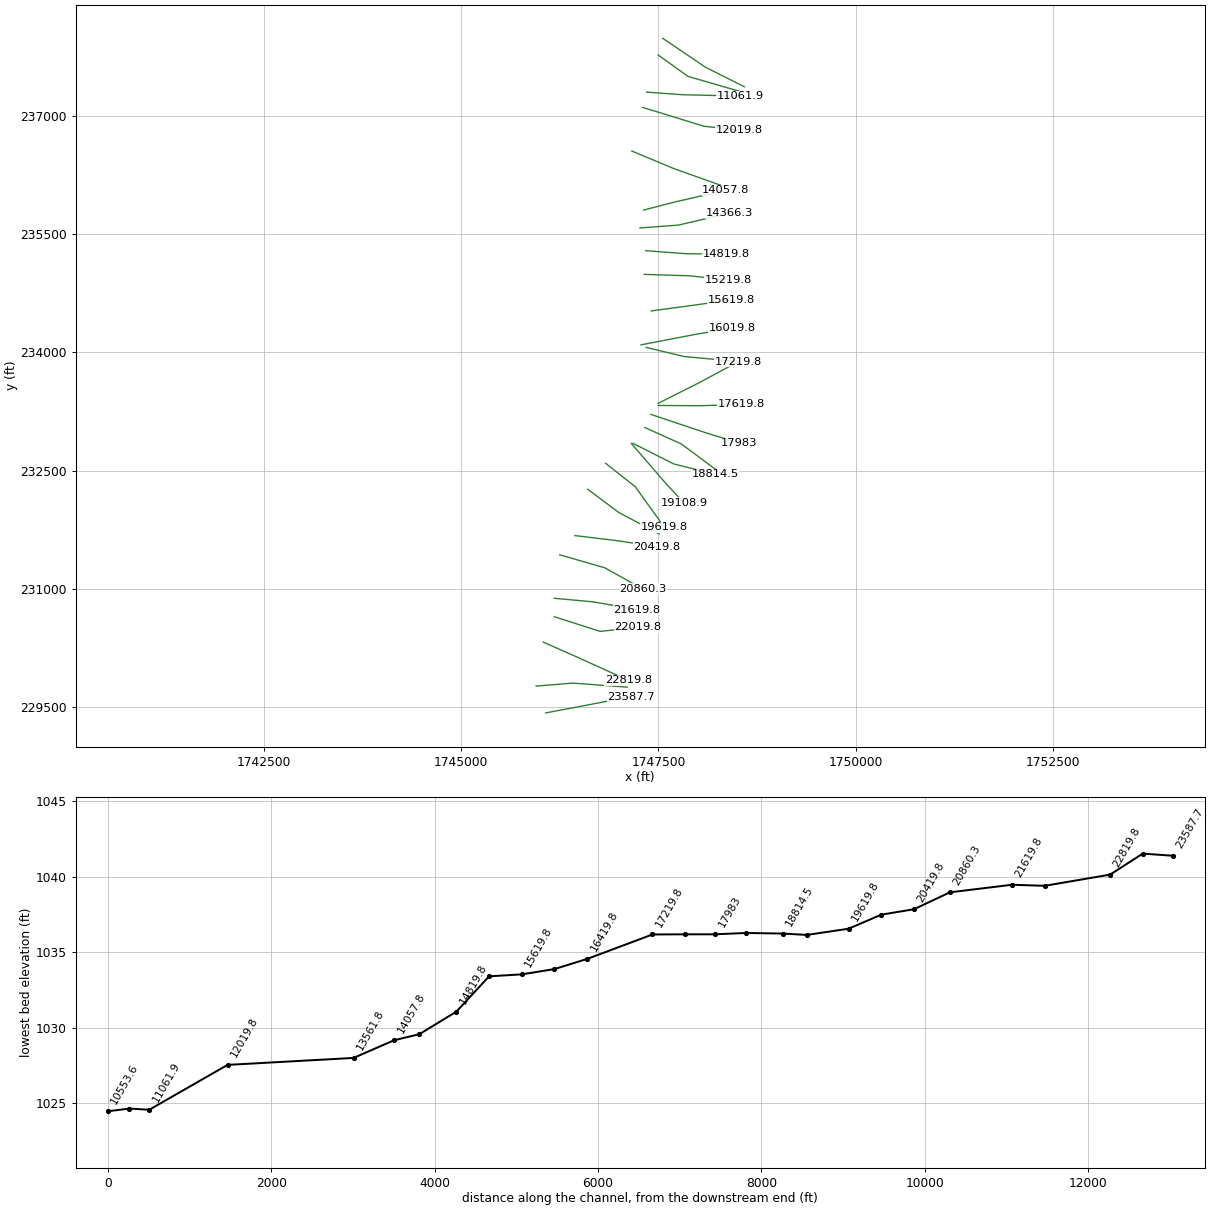
HEC-RAS study RotingCr.prj: RotingCr

--- RotingCr.g01 (geometry) --- (continued)

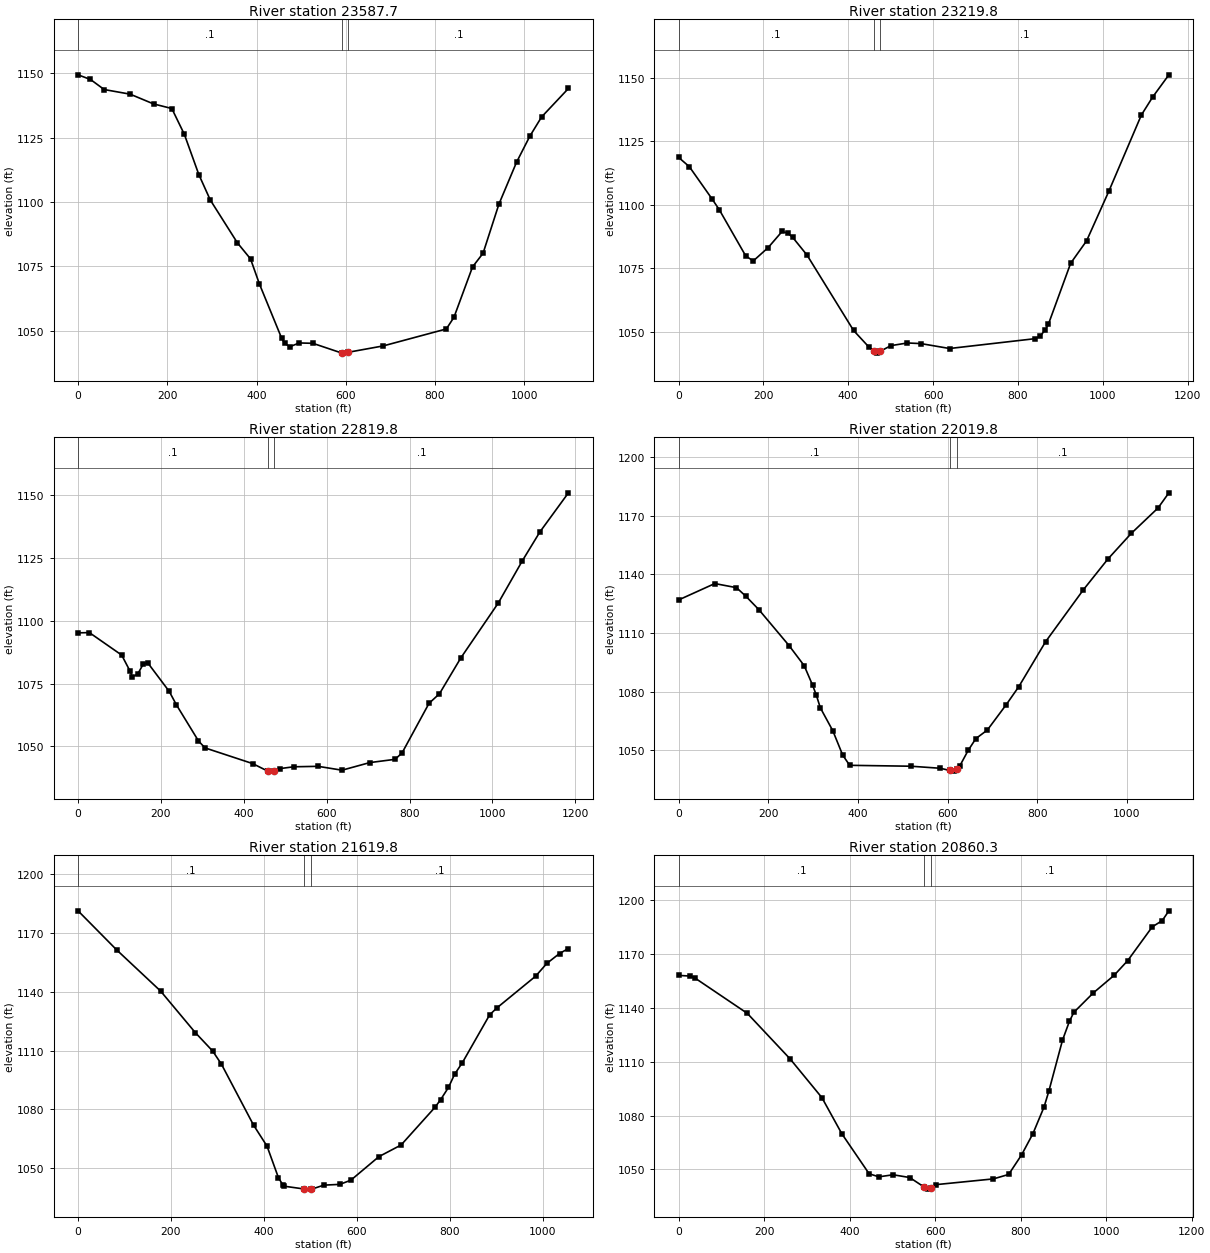
Type RM Length L Ch R = 1 ,23587.7,369.388,367.919,361.895
XS GIS Cut Line= 3
     1746072.557      229426.236     1746666.572      229538.436
     1747151.946      229632.433
#Sta/Elev= 30
       0 1149.36    27.8 1147.56    58.6 1143.65   116.7 1141.86   169.2 1138.07
   210.1 1136.29   238.3 1126.23   270.6 1110.68   296.3 1100.80   357.1 1084.17
   386.5 1077.95   406.4 1068.23   456.1 1047.23   462.8 1045.25   474.6 1043.87
   495.6 1045.34   526.1 1045.20   590.7 1041.44   594.6 1041.39   605.7 1041.73
   683.9 1044.19   825.3 1050.77   842.4 1055.30   884.0 1074.84   907.6 1080.14
   943.1 1099.18   982.6 1115.44  1012.6 1125.61  1038.8 1133.02  1098.9 1144.07
#Mann= 3 , 0 , 0
       0     0.1       0   590.7   0.045       0   605.7     0.1       0
Bank Sta=   590.7,   605.7
Exp/Cntr=0.3,0.1

Type RM Length L Ch R = 1 ,23219.8,406.849,400,394.829
XS GIS Cut Line= 3
     1745950.247      229765.951     1746416.044      229804.139
     1747102.422      229752.792
#Sta/Elev= 30
       0 1118.60    25.5 1114.92    78.6 1102.33    96.0 1098.00   158.4 1079.79
   176.1 1077.81   211.3 1083.08   244.0 1089.41   257.3 1088.78   269.2 1087.07
   302.9 1080.11   412.6 1050.44   449.6 1043.76   459.9 1042.47   467.4 1041.53
   474.9 1042.22   500.6 1044.48   539.6 1045.53   571.4 1045.28   638.8 1043.35
   840.8 1047.23   852.7 1048.27   864.6 1050.78   871.6 1052.85   924.2 1076.91
   961.7 1085.72  1013.9 1105.16  1090.9 1135.28  1117.5 1142.35  1155.7 1151.08
#Mann= 3 , 0 , 0
       0     0.1       0   459.9   0.045       0   474.9     0.1       0
Bank Sta=   459.9,   474.9
Exp/Cntr=0.3,0.1

Type RM Length L Ch R = 1 ,22819.8,799.001,800,807.647
XS GIS Cut Line= 3
     1746039.259      230324.571     1746465.617      230135.419
     1747118.462      229839.119
#Sta/Elev= 30
       0 1095.23    27.3 1095.33   105.3 1086.37   125.3 1080.03   131.2 1077.64
   144.2 1078.90   157.2 1082.73   167.9 1083.35   220.1 1071.88   237.4 1066.54
   290.6 1052.17   306.3 1049.40   421.4 1043.14   457.8 1040.14   458.9 1040.14
   473.9 1040.14   488.5 1041.17   520.5 1041.87   579.2 1042.05   637.0 1040.51
   703.9 1043.54   765.0 1044.84   781.9 1047.39   847.0 1067.16   872.2 1070.97
   923.7 1085.24  1014.0 1107.09  1072.4 1124.00  1114.5 1135.43  1183.4 1151.02
#Mann= 3 , 0 , 0
       0     0.1       0   458.9   0.045       0   473.9     0.1       0
Bank Sta=   458.9,   473.9
Exp/Cntr=0.3,0.1

Type RM Length L Ch R = 1 ,22019.8,394.807,400,393.11
XS GIS Cut Line= 3
     1746178.639      230646.582     1746762.338      230459.468
     1747239.908      230513.834
#Sta/Elev= 30
       0 1126.87    80.9 1135.27   129.2 1133.17   150.4 1128.74   179.1 1121.95
   246.5 1103.57   280.3 1093.29   299.1 1083.27   307.4 1078.18   316.2 1071.79
   344.1 1060.03   366.1 1047.61   381.7 1042.37   518.2 1041.91   583.8 1040.86
   605.5 1039.73   615.4 1039.40   620.5 1040.56   627.3 1042.07   646.0 1050.02
   663.2 1056.05   688.7 1060.39   731.1 1073.45   758.8 1082.55   818.5 1105.51
   902.8 1132.07   957.6 1147.81  1009.7 1160.91  1069.4 1173.90  1093.6 1181.64
#Mann= 3 , 0 , 0
       0     0.1       0   605.5   0.045       0   620.5     0.1       0
Bank Sta=   605.5,   620.5
Exp/Cntr=0.3,0.1

Type RM Length L Ch R = 1 ,21619.8,764.133,759.563,748.883
XS GIS Cut Line= 3
     1746180.877      230879.730     1746672.577      230834.522
     1747225.872      230737.233
#Sta/Elev= 30
       0 1181.07    82.9 1161.24   177.7 1140.24   252.2 1119.16   289.9 1109.69
   308.7 1103.02   377.8 1072.03   406.8 1061.33   431.3 1045.31   440.6 1041.69
   443.2 1040.98   486.3 1039.55   501.3 1039.48   503.1 1039.47   529.0 1041.50
   563.6 1041.89   587.3 1044.03   647.6 1056.00   695.4 1061.93   768.2 1081.06
   780.6 1085.03   797.4 1091.22   810.5 1097.88   827.5 1103.89   886.1 1128.18
   901.6 1131.67   984.9 1147.80  1009.3 1154.35  1036.4 1159.35  1055.6 1161.90
#Mann= 3 , 0 , 0
       0     0.1       0   486.3   0.045       0   501.3     0.1       0
Bank Sta=   486.3,   501.3
Exp/Cntr=0.3,0.1

Type RM Length L Ch R = 1 ,20860.3,437.741,440.437,445.897
XS GIS Cut Line= 3
     1746249.324      231430.975     1746818.905      231267.001
     1747302.472      230996.909
#Sta/Elev= 30
       0 1158.12    27.8 1157.73    38.5 1156.64   160.8 1136.96   260.7 1111.62
   335.3 1089.96   381.8 1069.86   445.7 1047.53   468.5 1045.83   501.8 1046.97
   540.6 1045.44   574.3 1040.13   583.3 1038.97   589.3 1039.79   601.0 1041.45
   736.1 1044.67   771.9 1047.15   802.2 1058.07   828.7 1069.91   854.6 1084.70
   865.7 1093.40   897.8 1121.97   914.0 1132.51   924.4 1137.54   969.6 1148.29
  1018.5 1158.15  1050.2 1166.33  1107.6 1185.14  1131.1 1188.69  1146.6 1194.11
#Mann= 3 , 0 , 0
       0     0.1       0   574.3   0.045       0   589.3     0.1       0
Bank Sta=   574.3,   589.3
Exp/Cntr=0.3,0.1

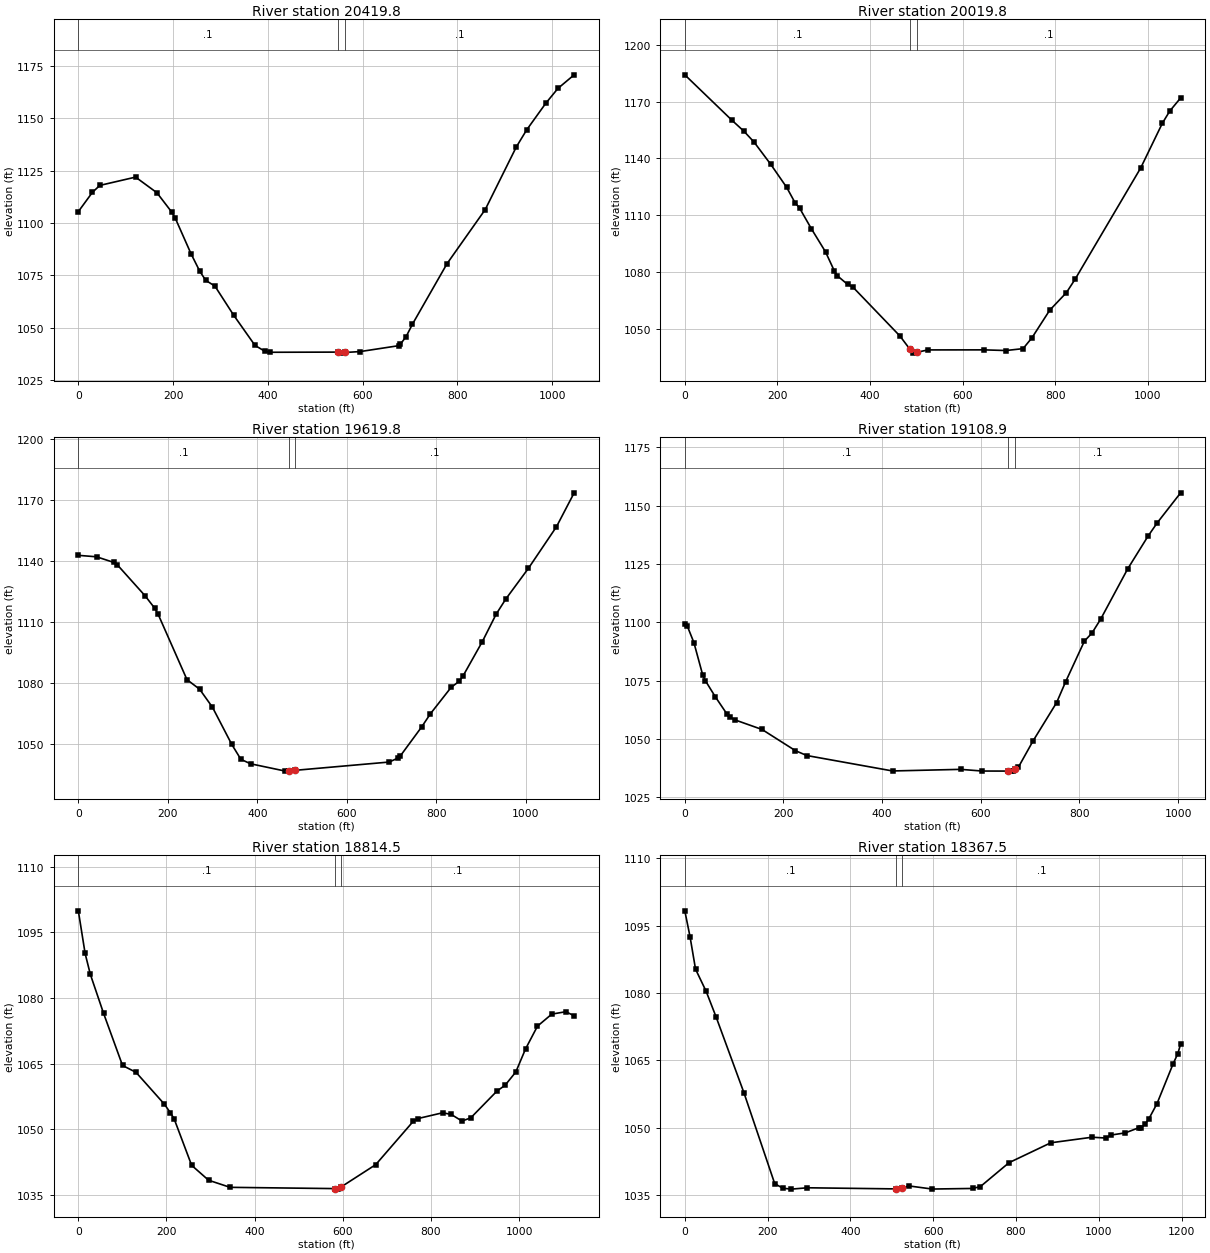
Type RM Length L Ch R = 1 ,20419.8,411.869,400,392.708
XS GIS Cut Line= 3
     1746443.008      231674.566     1746994.519      231608.142
     1747479.546      231533.118
#Sta/Elev= 30
       0 1105.43    29.8 1114.65    45.4 1117.94   120.8 1121.90   165.8 1114.44
   197.1 1105.20   204.5 1102.32   237.9 1085.25   256.3 1076.93   269.0 1072.56
   288.2 1069.87   327.7 1056.00   372.8 1041.53   393.3 1038.78   404.2 1038.26
     548 1038.34   559.1 1037.85     563 1038.16   594.9 1038.60   675.9 1041.40
   679.5 1042.08   691.8 1045.78   705.0 1051.65   778.1 1080.59   858.7 1106.43
   924.2 1136.29   946.0 1144.42   986.6 1157.21  1012.1 1164.26  1046.3 1170.74
#Mann= 3 , 0 , 0
       0     0.1       0     548   0.045       0     563     0.1       0
Bank Sta=     548,     563
Exp/Cntr=0.3,0.1

Type RM Length L Ch R = 1 ,20019.8,400.645,400,389.078
XS GIS Cut Line= 3
     1746603.243      232262.838     1746998.501      231966.940
     1747508.123      231697.190
#Sta/Elev= 30
       0 1184.07   102.2 1160.04   127.6 1154.38   149.5 1148.65   185.5 1136.94
   219.9 1124.81   237.9 1116.76   247.7 1113.91   273.3 1102.98   303.8 1090.82
   322.8 1080.81   329.4 1078.21   351.7 1073.64   362.4 1072.40   464.6 1046.46
   486.2 1039.46   492.4 1037.49   501.2 1037.95   524.8 1039.18   646.2 1039.21
   693.4 1038.86   730.3 1039.86   749.5 1045.59   787.8 1060.10   823.8 1069.34
   842.7 1076.45   984.2 1135.02  1031.0 1158.59  1046.9 1164.97  1070.4 1171.90
#Mann= 3 , 0 , 0
       0     0.1       0   486.2   0.045       0   501.2     0.1       0
Bank Sta=   486.2,   501.2
Exp/Cntr=0.3,0.1

Type RM Length L Ch R = 1 ,19619.8,514.388,510.915,514.515
XS GIS Cut Line= 3
     1746831.144      232591.385     1747205.649      232294.915
     1747572.591      231782.823
#Sta/Elev= 30
       0 1142.66    40.7 1141.95    78.9 1139.20    87.2 1137.97   149.2 1122.75
   170.9 1116.58   178.2 1113.72   242.7 1081.55   270.9 1076.84   299.6 1067.98
   342.6 1049.75   363.1 1042.36   384.8 1040.17   462.6 1036.56   470.1 1036.70
   485.1 1036.97   694.5 1041.03   714.5 1043.04   719.5 1044.09   767.1 1058.34
   786.6 1064.79   832.8 1077.76   850.4 1080.66   859.7 1083.49   902.4 1100.21
   933.2 1113.68   954.8 1121.15  1005.4 1136.27  1068.1 1156.73  1107.6 1173.40
#Mann= 3 , 0 , 0
       0     0.1       0   470.1   0.045       0   485.1     0.1       0
Bank Sta=   470.1,   485.1
Exp/Cntr=0.3,0.1

Type RM Length L Ch R = 1 ,19108.9,284.625,294.381,307.313
XS GIS Cut Line= 3
     1747156.415      232842.998     1747587.618      232342.534
     1747822.210      232090.068
#Sta/Elev= 30
       0 1099.07     5.0 1098.42    18.4 1091.33    36.3 1077.41    41.9 1074.89
    61.7 1068.10    85.1 1060.76    91.1 1059.47   101.2 1058.17   156.6 1054.02
   224.4 1044.91   247.4 1042.84   421.2 1036.22   559.2 1036.91   602.7 1036.19
   654.9 1036.17   660.4 1036.15   665.4 1036.21   669.9 1037.17   676.2 1037.80
   706.0 1049.10   753.8 1065.55   772.2 1074.56   810.1 1091.92   825.4 1095.37
   842.9 1101.28   898.0 1122.97   939.3 1137.02   958.1 1142.78  1005.2 1155.55
#Mann= 3 , 0 , 0
       0     0.1       0   654.9   0.045       0   669.9     0.1       0
Bank Sta=   654.9,   669.9
Exp/Cntr=0.3,0.1

Type RM Length L Ch R = 1 ,18814.5,441.501,447.039,440.216
XS GIS Cut Line= 3
     1747176.523      232845.232     1747692.220      232583.795
     1748222.743      232451.101
#Sta/Elev= 30
       0 1099.96    15.4 1090.19    27.3 1085.40    57.2 1076.51   100.3 1064.55
   130.9 1062.98   195.5 1055.66   208.7 1053.74   217.2 1052.38   257.1 1041.69
   295.5 1038.28   344.3 1036.65     582 1036.36   589.0 1036.24     597 1036.79
   674.8 1041.85   760.3 1051.81   771.0 1052.41   826.5 1053.72   846.0 1053.35
   870.4 1051.83   890.4 1052.56   949.8 1058.69   968.3 1060.02   992.6 1063.06
  1014.6 1068.32  1041.8 1073.56  1074.2 1076.31  1106.1 1076.86  1125.0 1075.93
#Mann= 3 , 0 , 0
       0     0.1       0     582   0.045       0     597     0.1       0
Bank Sta=     582,     597
Exp/Cntr=0.3,0.1

Type RM Length L Ch R = 1 ,18367.5,378.24,384.498,393.908
XS GIS Cut Line= 3
     1747326.480      233045.380     1747787.972      232838.188
     1748342.782      232425.200
#Sta/Elev= 30
       0 1098.32    12.6 1092.58    25.9 1085.33    51.7 1080.34    75.6 1074.66
   142.7 1057.80   217.2 1037.49   237.0 1036.48   257.6 1036.28   295.8 1036.58
   510.3 1036.33   525.3 1036.56   540.7 1037.00   597.5 1036.30   695.5 1036.43
   714.1 1036.86   783.1 1042.18   883.9 1046.61   983.5 1047.85  1017.1 1047.67
  1029.1 1048.33  1063.8 1048.82  1097.5 1050.00  1100.7 1049.88  1111.9 1050.79
  1120.5 1051.90  1140.4 1055.33  1179.3 1064.20  1190.8 1066.51  1197.5 1068.62
#Mann= 3 , 0 , 0
       0     0.1       0   510.3   0.045       0   525.3     0.1       0
Bank Sta=   510.3,   525.3
Exp/Cntr=0.3,0.1

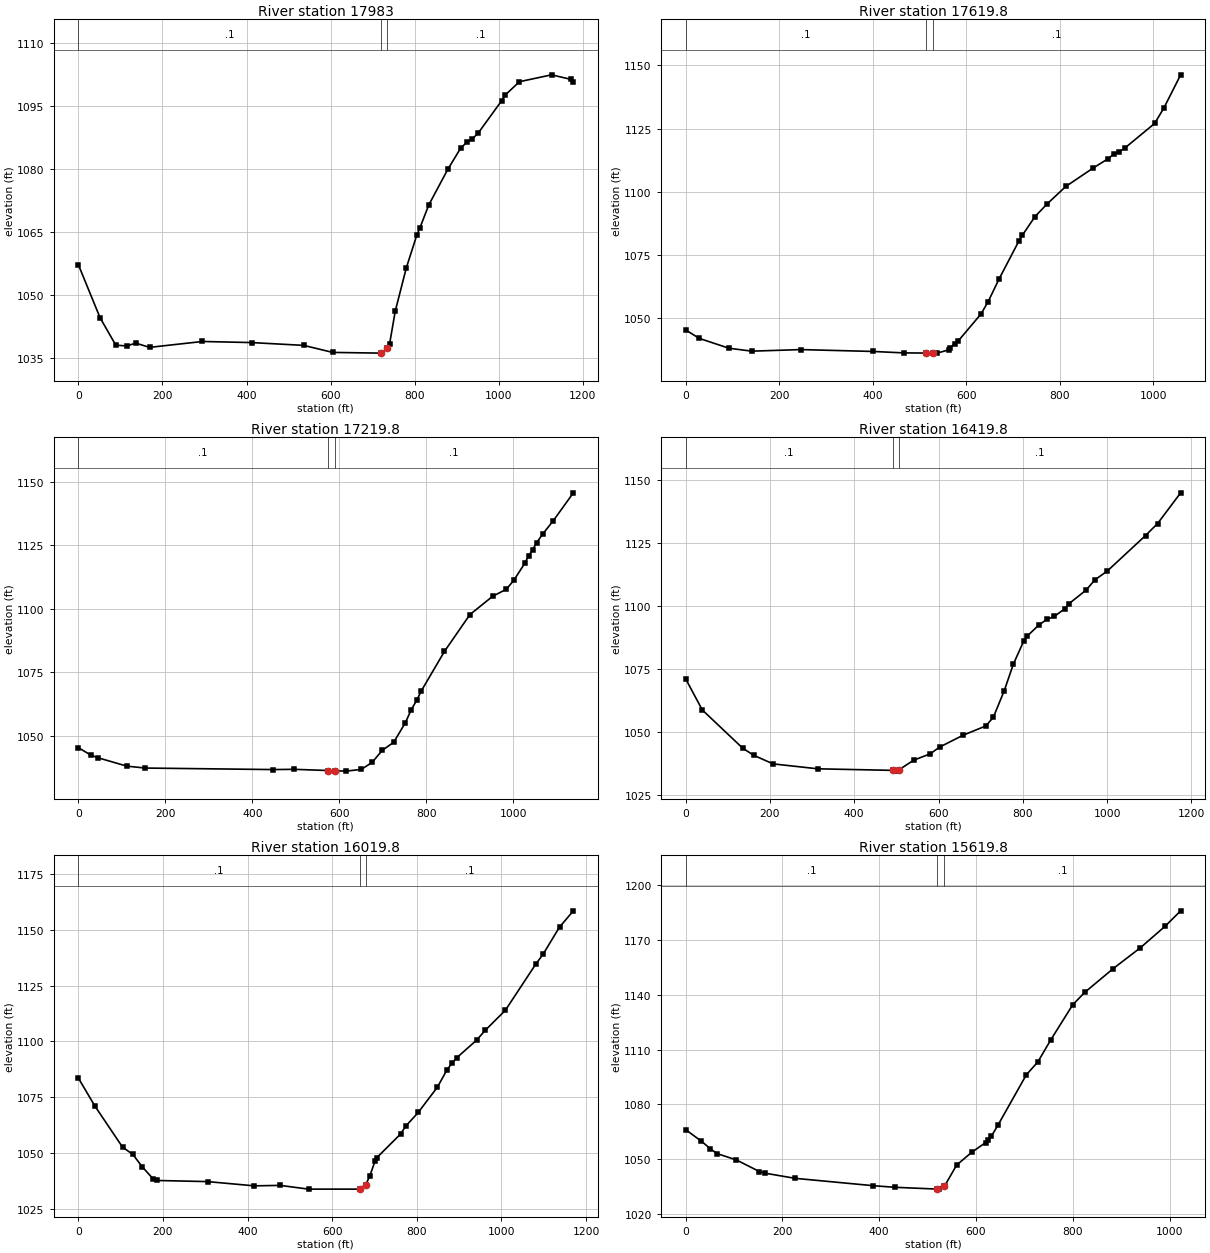
Type RM Length L Ch R = 1 ,17983,356.983,363.167,369.914
XS GIS Cut Line= 3
     1747404.412      233211.643     1748091.096      232981.608
     1748523.754      232847.467
#Sta/Elev= 30
       0 1057.26    51.7 1044.62    89.1 1038.09   115.2 1037.89   136.4 1038.57
   169.5 1037.56   295.3 1038.96   411.9 1038.70   536.2 1038.03   604.9 1036.36
   719.7 1036.19   734.7 1037.36   737.4 1037.47   740.2 1038.35   753.7 1046.18
   779.9 1056.43   804.7 1064.18   812.2 1065.94   833.5 1071.44   878.6 1079.88
   909.6 1084.99   924.1 1086.32   936.0 1087.03   950.9 1088.51  1007.0 1096.24
  1015.0 1097.54  1048.9 1100.72  1125.3 1102.36  1171.9 1101.27  1177.2 1100.67
#Mann= 3 , 0 , 0
       0     0.1       0   719.7   0.045       0   734.7     0.1       0
Bank Sta=   719.7,   734.7
Exp/Cntr=0.3,0.1

Type RM Length L Ch R = 1 ,17619.8,388.748,400,488.407
XS GIS Cut Line= 3
     1747495.632      233325.336     1748017.127      233321.841
     1748553.569      233338.208
#Sta/Elev= 30
       0 1045.40    29.0 1042.04    92.6 1038.13   141.2 1036.97   246.2 1037.59
   401.2 1036.85   466.4 1036.28     514 1036.22     529 1036.20   537.7 1036.19
   563.2 1037.53   566.0 1038.34   575.1 1039.99   582.3 1040.91   631.3 1051.65
   646.7 1056.57   670.5 1065.70   712.6 1080.61   719.6 1082.77   746.7 1090.18
   772.6 1095.20   812.7 1102.13   869.9 1109.27   903.2 1113.12   915.6 1115.02
   926.3 1115.80   939.1 1117.37  1002.5 1127.05  1022.2 1133.14  1058.2 1146.30
#Mann= 3 , 0 , 0
       0     0.1       0     514   0.045       0     529     0.1       0
Bank Sta=     514,     529
Exp/Cntr=0.3,0.1

Type RM Length L Ch R = 1 ,17219.8,825.964,800,670.62
XS GIS Cut Line= 3
     1747496.015      233352.399     1748015.452      233614.025
     1748505.880      233877.439
#Sta/Elev= 30
       0 1045.42    29.1 1042.45    44.7 1041.46   111.7 1038.14   153.8 1037.39
   448.8 1036.79   495.6 1036.89   574.1 1036.42   589.1 1036.33   616.2 1036.18
   650.9 1036.87   675.7 1039.62   698.9 1044.35   725.3 1047.53   752.2 1055.27
   765.0 1060.13   779.1 1064.32   788.2 1067.57   841.9 1083.23   900.5 1097.72
   952.5 1104.86   984.4 1107.70  1001.6 1111.24  1026.7 1117.89  1035.2 1120.77
  1045.0 1123.28  1053.9 1126.01  1068.7 1129.55  1092.5 1134.69  1138.3 1145.57
#Mann= 3 , 0 , 0
       0     0.1       0   574.1   0.045       0   589.1     0.1       0
Bank Sta=   574.1,   589.1
Exp/Cntr=0.3,0.1

Type RM Length L Ch R = 1 ,16419.8,373.595,400,406.92
XS GIS Cut Line= 3
     1747343.570      234061.808     1747828.845      233944.925
     1748501.411      233884.142
#Sta/Elev= 30
       0 1071.21    39.6 1058.82   135.9 1043.60   161.8 1040.83   207.5 1037.43
   313.7 1035.48   491.7 1034.86   501.1 1034.56   506.7 1035.16   541.5 1038.92
   580.1 1041.41   603.0 1044.13   657.0 1048.70   712.4 1052.50   730.1 1055.93
   756.1 1066.53   777.5 1076.97   802.3 1086.21   809.6 1087.99   837.4 1092.43
   856.8 1094.72   874.8 1095.92   900.2 1099.06   908.9 1100.90   950.3 1106.39
   971.0 1110.45  1000.3 1113.91  1091.1 1128.01  1119.7 1132.77  1174.5 1144.96
#Mann= 3 , 0 , 0
       0     0.1       0   491.7   0.045       0   506.7     0.1       0
Bank Sta=   491.7,   506.7
Exp/Cntr=0.3,0.1

Type RM Length L Ch R = 1 ,16019.8,401.059,400,399.509
XS GIS Cut Line= 3
     1747279.297      234094.158     1747939.209      234221.387
     1748429.852      234306.014
#Sta/Elev= 30
       0 1083.64    39.0 1071.14   104.7 1052.65   128.9 1049.45   150.6 1043.99
   177.3 1038.38   185.4 1037.76   305.5 1037.26   415.9 1035.36   477.1 1035.56
   544.2 1033.89   664.6 1033.89   679.6 1035.96   689.0 1039.81   701.7 1046.64
   705.9 1048.04   761.5 1058.54   773.9 1062.07   803.3 1068.19   848.7 1079.53
   870.8 1087.08   883.1 1090.27   894.6 1092.72   941.3 1100.57   962.1 1105.04
  1009.2 1113.90  1081.3 1134.63  1098.2 1138.94  1137.3 1151.17  1170.0 1158.45
#Mann= 3 , 0 , 0
       0     0.1       0   664.6   0.045       0   679.6     0.1       0
Bank Sta=   664.6,   679.6
Exp/Cntr=0.3,0.1

Type RM Length L Ch R = 1 ,15619.8,403.803,400,394.403
XS GIS Cut Line= 3
     1747408.993      234524.224     1747931.123      234594.717
     1748422.250      234662.972
#Sta/Elev= 30
       0 1066.13    32.8 1059.77    50.8 1055.73    64.5 1053.05   104.9 1049.53
   152.6 1043.16   163.1 1042.32   226.1 1039.46   387.6 1035.42   431.9 1034.55
   519.4 1033.57   522.0 1033.54   524.0 1033.60   534.4 1035.29   535.5 1035.47
   559.9 1046.72   591.0 1053.71   619.9 1059.07   623.9 1060.49   631.8 1062.58
   645.2 1068.56   703.8 1096.14   727.7 1103.26   754.7 1115.47   799.7 1134.54
   824.4 1141.31   883.6 1154.42   939.2 1165.72   990.6 1177.58  1022.7 1186.02
#Mann= 3 , 0 , 0
       0     0.1       0   519.4   0.045       0   534.4     0.1       0
Bank Sta=   519.4,   534.4
Exp/Cntr=0.3,0.1

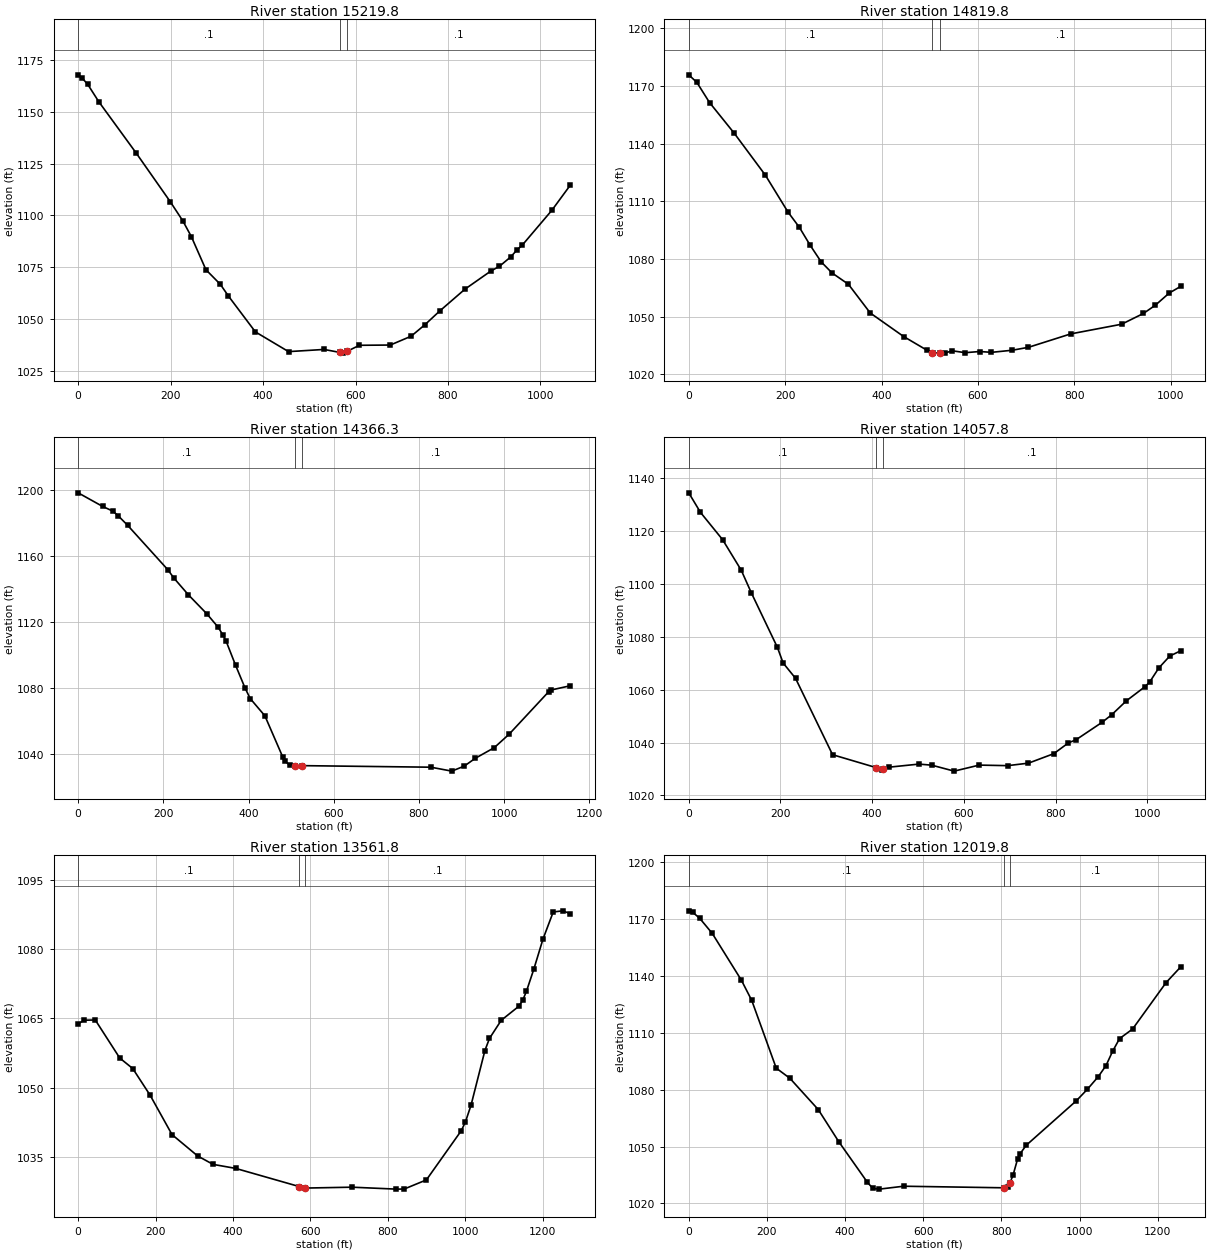
Type RM Length L Ch R = 1 ,15219.8,401.117,400,386.887
XS GIS Cut Line= 3
     1747319.512      234987.843     1747893.339      234969.486
     1748380.763      234916.801
#Sta/Elev= 30
       0 1167.99     9.3 1166.27    20.8 1163.35    44.5 1155.04   125.8 1130.08
   199.1 1106.69   226.4 1097.38   244.9 1089.74   276.4 1073.74   307.6 1066.67
   325.1 1061.00   383.4 1043.68   455.1 1034.14   532.0 1035.19   566.6 1033.73
   573.4 1033.41   581.6 1034.27   608.5 1037.20   675.2 1037.32   720.3 1041.59
   750.5 1047.22   781.8 1053.72   836.7 1064.34   892.6 1073.09   911.1 1075.37
   935.4 1079.87   949.7 1083.42   960.3 1085.53  1024.6 1102.45  1064.4 1114.58
#Mann= 3 , 0 , 0
       0     0.1       0   566.6   0.045       0   581.6     0.1       0
Bank Sta=   566.6,   581.6
Exp/Cntr=0.3,0.1

Type RM Length L Ch R = 1 ,14819.8,446.226,453.534,459.07
XS GIS Cut Line= 3
     1747339.156      235288.245     1747850.832      235249.675
     1748358.339      235244.192
#Sta/Elev= 30
       0 1175.85    16.8 1171.92    43.1 1161.44    94.6 1145.39   158.9 1123.66
   205.9 1104.45   229.4 1096.54   252.1 1087.09   274.8 1078.52   297.3 1072.77
   331.2 1066.89   376.5 1051.95   445.7 1039.72   493.5 1032.67   505.6 1031.30
   507.4 1031.07   520.6 1031.23   531.3 1031.15   547.0 1032.27   573.6 1031.30
   603.4 1031.91   628.0 1031.48   671.2 1032.58   704.7 1034.10   792.4 1041.08
   897.9 1046.11   943.0 1051.69   967.8 1055.98   996.7 1062.33  1020.7 1065.83
#Mann= 3 , 0 , 0
       0     0.1       0   505.6   0.045       0   520.6     0.1       0
Bank Sta=   505.6,   520.6
Exp/Cntr=0.3,0.1

Type RM Length L Ch R = 1 ,14366.3,307.861,308.455,308.432
XS GIS Cut Line= 3
     1747264.416      235576.336     1747753.210      235613.005
     1748400.872      235763.116
#Sta/Elev= 30
       0 1198.30    57.3 1190.08    81.7 1187.17    94.2 1184.32   115.9 1178.68
   210.2 1151.77   225.2 1146.48   258.9 1136.43   302.3 1124.88   328.7 1116.79
   340.5 1111.81   347.5 1108.24   369.6 1093.72   391.6 1080.06   403.8 1073.60
   438.3 1063.12   480.4 1038.05   484.8 1035.88   496.9 1033.07   510.1 1032.98
   525.1 1032.91   828.0 1031.96   877.0 1029.58   906.4 1032.63   931.9 1037.32
   976.6 1043.78  1011.6 1051.96  1104.4 1077.71  1110.9 1078.80  1155.0 1081.33
#Mann= 3 , 0 , 0
       0     0.1       0   510.1   0.045       0   525.1     0.1       0
Bank Sta=   510.1,   525.1
Exp/Cntr=0.3,0.1

Type RM Length L Ch R = 1 ,14057.8,510.106,496.041,483.445
XS GIS Cut Line= 3
     1747310.575      235803.331     1747714.914      235907.820
     1748353.953      236053.563
#Sta/Elev= 30
       0 1134.43    25.6 1127.03    73.9 1116.70   114.5 1105.15   136.2 1096.71
   193.4 1075.95   205.8 1070.07   232.8 1064.30   313.6 1035.39   409.1 1030.49
   421.2 1029.79   424.1 1029.96   436.5 1030.67   502.0 1031.84   529.9 1031.43
   578.7 1029.18   633.4 1031.46   695.4 1031.25   740.8 1032.20   795.9 1035.78
   827.8 1039.86   844.5 1041.05   901.0 1047.61   922.1 1050.48   954.1 1055.75
   995.1 1061.16  1005.0 1062.88  1025.1 1068.23  1048.8 1072.69  1072.9 1074.73
#Mann= 3 , 0 , 0
       0     0.1       0   409.1   0.045       0   424.1     0.1       0
Bank Sta=   409.1,   424.1
Exp/Cntr=0.3,0.1

Type RM Length L Ch R = 1 ,13561.8,1540.905,1541.97,1546.463
XS GIS Cut Line= 3
     1747163.117      236551.793     1747689.739      236331.250
     1748349.485      236096.013
#Sta/Elev= 30
       0 1063.82    15.5 1064.62    44.3 1064.66   107.6 1056.41   141.1 1054.14
   185.9 1048.37   242.6 1039.82   308.9 1035.19   348.7 1033.37   406.6 1032.51
   571.5 1028.56   586.5 1028.24   707.6 1028.43   822.1 1028.01   842.4 1028.03
   899.8 1030.01   989.9 1040.67  1000.6 1042.56  1015.1 1046.19  1051.0 1058.05
  1062.8 1060.67  1093.2 1064.60  1138.4 1067.62  1148.6 1068.93  1158.3 1070.88
  1177.5 1075.71  1201.0 1082.19  1227.5 1088.07  1251.9 1088.32  1271.4 1087.72
#Mann= 3 , 0 , 0
       0     0.1       0   571.5   0.045       0   586.5     0.1       0
Bank Sta=   571.5,   586.5
Exp/Cntr=0.3,0.1

Type RM Length L Ch R = 1 ,12019.8,952.488,957.882,958.029
XS GIS Cut Line= 3
     1747300.932      237104.949     1748079.004      236865.875
     1748521.695      236818.854
#Sta/Elev= 30
       0 1174.21    10.4 1173.38    27.7 1170.36    60.1 1162.33   134.6 1137.70
   161.3 1126.97   223.9 1091.30   258.8 1085.97   331.5 1069.45   383.9 1052.55
   457.3 1031.11   471.1 1027.91   487.9 1027.55   549.8 1029.08   806.5 1028.25
   817.6 1028.75   821.5 1030.69   829.7 1034.77   841.5 1043.41   846.6 1045.83
   863.6 1050.65   991.6 1074.06  1020.1 1080.17  1048.1 1086.86  1067.7 1092.63
  1084.7 1100.21  1102.5 1106.88  1135.7 1111.90  1221.6 1136.41  1259.2 1144.72
#Mann= 3 , 0 , 0
       0     0.1       0   806.5   0.045       0   821.5     0.1       0
Bank Sta=   806.5,   821.5
Exp/Cntr=0.3,0.1

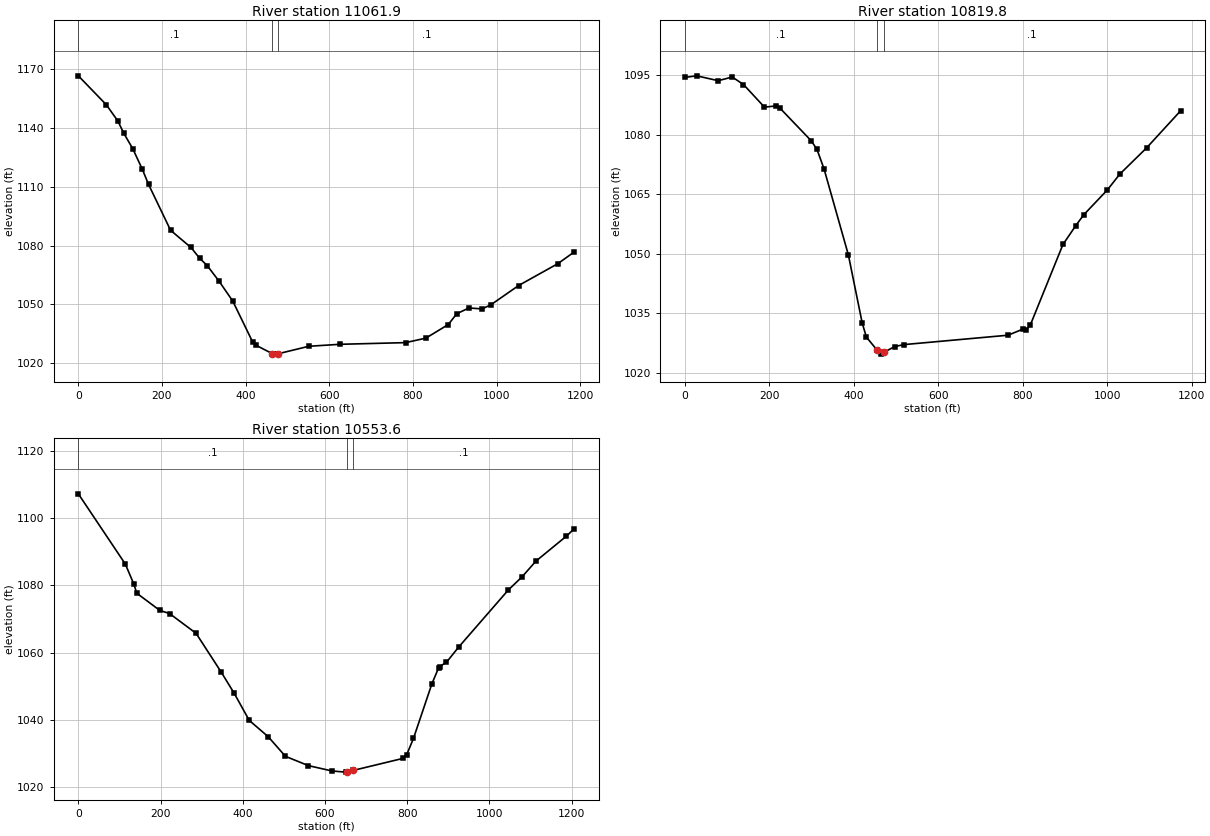
Type RM Length L Ch R = 1 ,11061.9,255.412,242.118,236.842
XS GIS Cut Line= 3
     1747350.972      237299.133     1747802.593      237266.338
     1748534.925      237248.868
#Sta/Elev= 30
       0 1166.65    66.9 1151.88    94.4 1143.63   108.5 1137.38   130.2 1129.41
   153.1 1118.89   167.8 1111.24   220.5 1087.80   269.3 1079.02   290.2 1073.49
   308.1 1069.76   336.0 1061.94   369.2 1051.65   416.5 1030.87   424.7 1029.11
   463.2 1024.88   471.6 1024.58   478.2 1024.80   551.0 1028.59   625.7 1029.60
   782.2 1030.45   830.6 1032.73   884.3 1039.67   904.7 1045.21   933.8 1048.15
   965.2 1047.66   986.8 1049.84  1052.4 1059.59  1146.6 1070.80  1185.3 1076.72
#Mann= 3 , 0 , 0
       0     0.1       0   463.2   0.045       0   478.2     0.1       0
Bank Sta=   463.2,   478.2
Exp/Cntr=0.3,0.1

Type RM Length L Ch R = 1 ,10819.8,264.79,266.204,261.902
XS GIS Cut Line= 3
     1747496.010      237769.888     1747872.147      237499.498
     1748554.687      237300.968
#Sta/Elev= 30
       0 1094.43    28.2 1094.83    79.1 1093.60   112.2 1094.53   139.0 1092.64
   188.6 1086.94   215.9 1087.23   225.3 1086.69   299.6 1078.43   313.0 1076.27
   329.6 1071.41   387.3 1049.69   420.1 1032.50   430.0 1028.95   455.7 1025.63
   465.6 1024.66   470.7 1025.08   496.8 1026.55   518.7 1027.06   765.5 1029.43
   800.9 1030.98   808.5 1030.75   818.4 1032.06   895.5 1052.31   925.3 1056.98
   944.5 1059.77  1000.6 1066.06  1030.2 1070.06  1093.3 1076.64  1174.1 1086.02
#Mann= 3 , 0 , 0
       0     0.1       0   455.7   0.045       0   470.7     0.1       0
Bank Sta=   455.7,   470.7
Exp/Cntr=0.3,0.1

Type RM Length L Ch R = 1 ,10553.6,639.8,637.605,632.306
XS GIS Cut Line= 3
     1747554.105      237981.690     1748094.784      237615.279
     1748588.778      237366.679
#Sta/Elev= 30
       0 1107.14   114.4 1086.26   134.8 1080.39   142.3 1077.61   198.1 1072.52
   221.9 1071.58   286.4 1065.71   347.5 1054.20   379.2 1047.89   415.9 1039.83
   461.8 1035.01   503.9 1029.17   559.7 1026.41   616.9 1024.83   650.1 1024.48
   654.4 1024.60   669.4 1025.01   789.4 1028.55   799.0 1029.71   815.3 1034.50
   860.2 1050.75   876.4 1055.43   878.7 1055.84   895.3 1057.07   925.5 1061.66
  1046.1 1078.59  1079.8 1082.53  1113.0 1087.13  1186.4 1094.48  1206.2 1096.73
#Mann= 3 , 0 , 0
       0     0.1       0   654.4   0.045       0   669.4     0.1       0
Bank Sta=   654.4,   669.4
Exp/Cntr=0.3,0.1