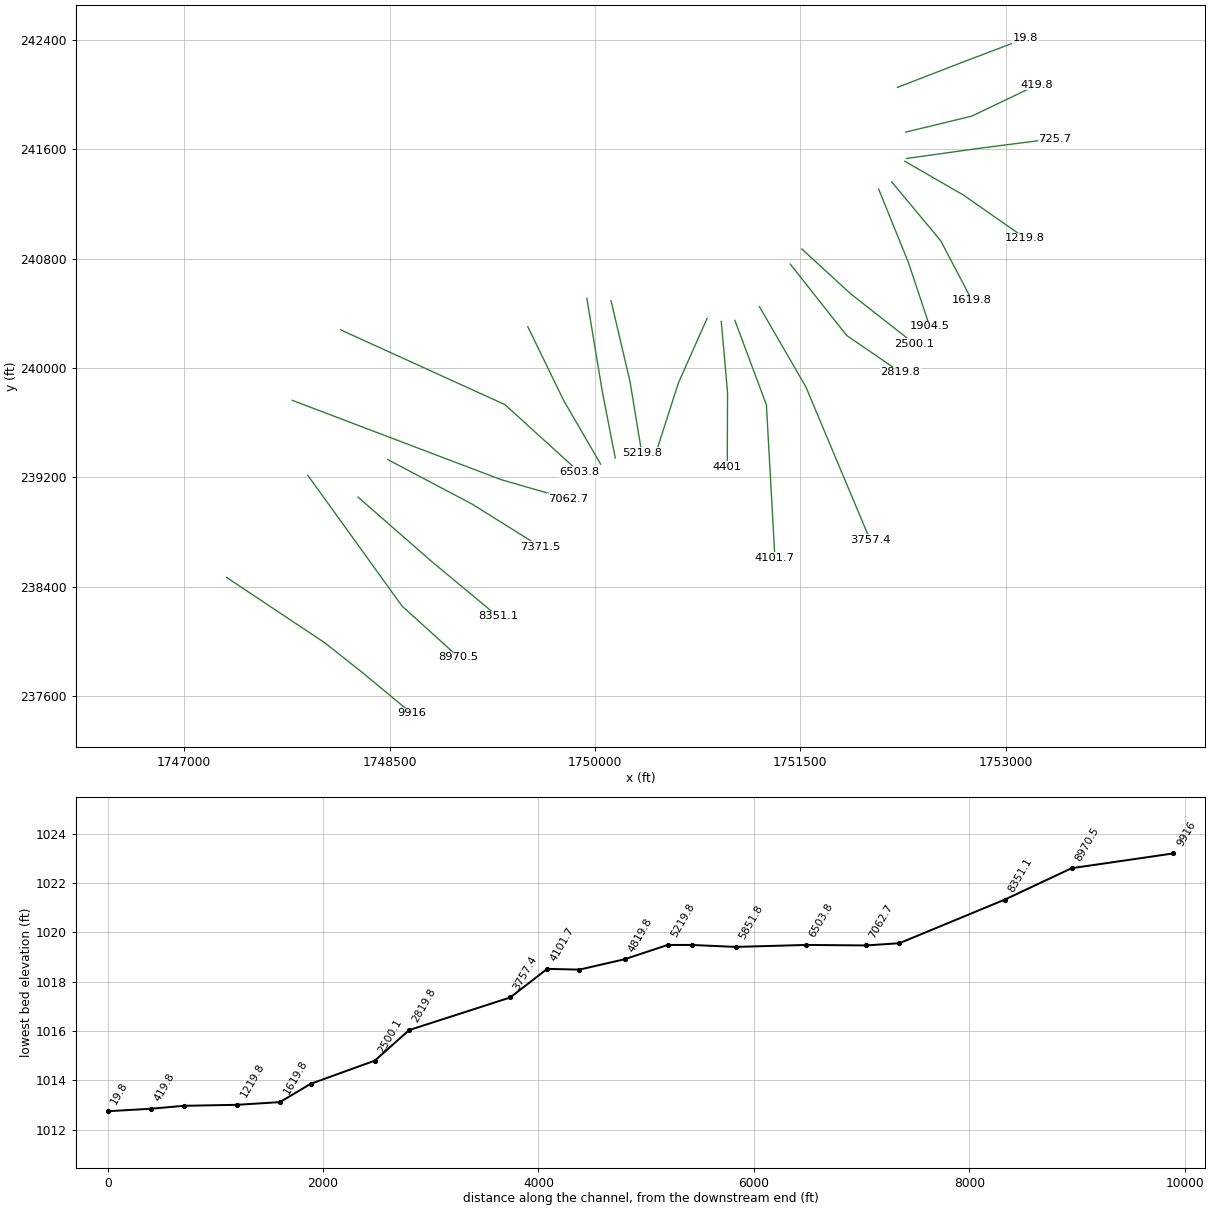
HEC-RAS study RotingCr.prj: RotingCr

--- RotingCr.g01 (geometry) --- (continued)

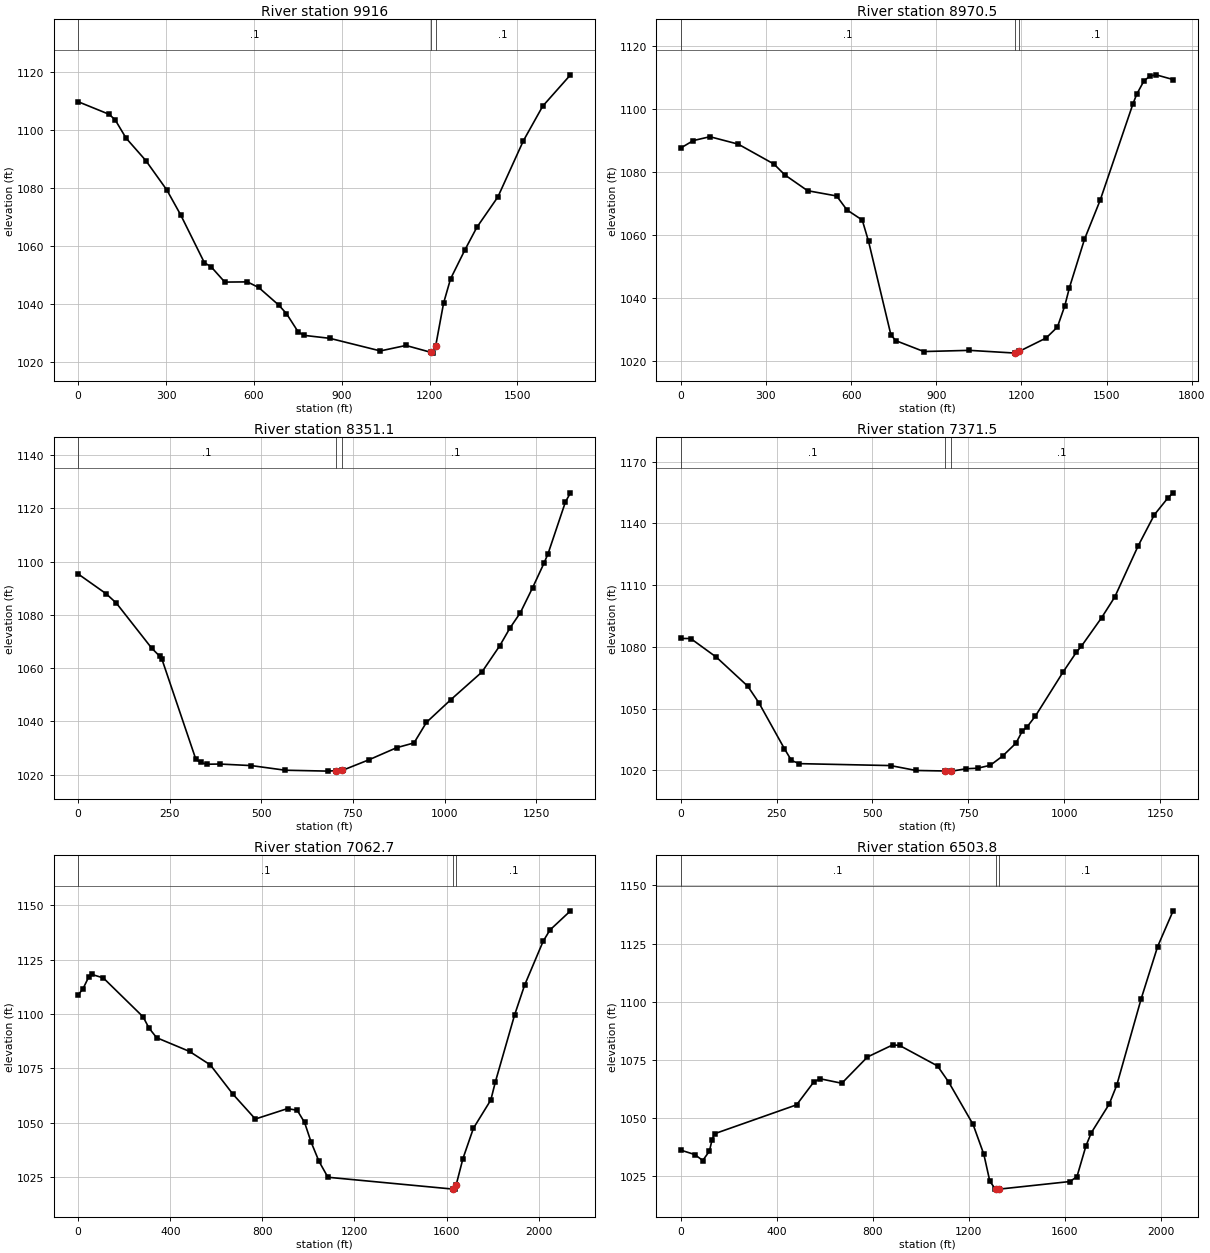
Type RM Length L Ch R = 1 ,9916,955.934,945.508,957.425
XS GIS Cut Line= 4
     1747308.341      238468.748     1748025.524      237990.627
     1748298.413      237774.403     1748661.155      237473.583
#Sta/Elev= 30
       0 1109.76   105.9 1105.42   126.1 1103.56   163.7 1097.22   230.9 1089.52
   302.7 1079.39   350.1 1070.80   431.1 1054.33   454.5 1052.88   500.8 1047.66
   577.8 1047.73   616.6 1045.80   685.0 1039.74   711.4 1036.81   752.0 1030.41
   772.8 1029.30   859.3 1028.30  1032.1 1023.96  1119.5 1025.84  1205.8 1023.44
  1211.9 1023.20  1220.8 1025.58  1248.0 1040.43  1271.6 1048.73  1320.3 1058.64
  1361.6 1066.52  1433.5 1076.99  1520.3 1096.28  1586.5 1108.23  1681.4 1119.02
#Mann= 3 , 0 , 0
       0     0.1       0  1205.8   0.045       0  1220.8     0.1       0
Bank Sta=  1205.8,  1220.8
Exp/Cntr=0.3,0.1

Type RM Length L Ch R = 1 ,8970.5,609.97,619.402,601.106
XS GIS Cut Line= 3
     1747902.642      239214.976     1748590.780      238258.732
     1749002.990      237884.760
#Sta/Elev= 30
       0 1087.62    43.8 1089.97   102.6 1091.20   202.3 1088.85   328.3 1082.53
   366.7 1079.09   446.7 1074.09   549.1 1072.42   585.3 1068.01   639.4 1064.78
   661.6 1058.01   740.5 1028.32   758.0 1026.54   856.4 1023.10  1017.1 1023.48
  1177.2 1022.62  1181.5 1022.60  1192.2 1023.15  1287.1 1027.39  1327.0 1030.87
  1353.0 1037.60  1369.4 1043.38  1422.4 1058.69  1477.9 1071.13  1592.8 1101.52
  1606.1 1104.61  1632.0 1108.91  1654.0 1110.47  1674.8 1110.82  1734.7 1109.32
#Mann= 3 , 0 , 0
       0     0.1       0  1177.2   0.045       0  1192.2     0.1       0
Bank Sta=  1177.2,  1192.2
Exp/Cntr=0.3,0.1

Type RM Length L Ch R = 1 ,8351.1,973.552,979.576,982.758
XS GIS Cut Line= 3
     1748269.053      239056.347     1748804.944      238586.723
     1749290.197      238182.943
#Sta/Elev= 30
       0 1095.36    76.5 1087.92   104.0 1084.46   200.6 1067.52   223.0 1064.42
   228.9 1063.26   321.2 1025.79   334.2 1024.57   352.0 1023.92   386.8 1023.99
   472.4 1023.41   565.1 1021.67   683.1 1021.33   704.3 1021.54   719.3 1021.69
   723.1 1021.72   794.2 1025.62   869.5 1030.14   916.7 1031.92   950.7 1039.65
  1017.4 1048.19  1102.0 1058.53  1150.7 1068.40  1178.4 1075.02  1206.9 1080.81
  1240.1 1090.12  1271.2 1099.33  1282.7 1103.04  1330.1 1122.46  1343.8 1125.83
#Mann= 3 , 0 , 0
       0     0.1       0   704.3   0.045       0   719.3     0.1       0
Bank Sta=   704.3,   719.3
Exp/Cntr=0.3,0.1

Type RM Length L Ch R = 1 ,7371.5,306.028,308.855,315.559
XS GIS Cut Line= 3
     1748485.772      239331.155     1749102.415      239004.960
     1749599.433      238693.485
#Sta/Elev= 30
       0 1084.06    25.9 1084.02    93.0 1074.93   174.7 1060.85   203.5 1052.85
   270.5 1030.39   288.7 1024.73   309.1 1023.20   547.1 1022.26   613.5 1019.88
   690.1 1019.63   705.1 1019.57   707.3 1019.56   744.2 1020.72   774.0 1020.97
   807.1 1022.39   839.2 1026.85   874.2 1033.14   890.8 1039.02   903.5 1041.13
   925.2 1046.39   996.9 1067.66  1031.8 1077.35  1045.1 1080.33  1097.5 1094.11
  1132.0 1104.22  1192.8 1129.00  1235.3 1144.21  1271.2 1152.52  1284.2 1154.86
#Mann= 3 , 0 , 0
       0     0.1       0   690.1   0.045       0   705.1     0.1       0
Bank Sta=   690.1,   705.1
Exp/Cntr=0.3,0.1

Type RM Length L Ch R = 1 ,7062.7,561.051,558.831,545.93
XS GIS Cut Line= 3
     1747790.195      239763.704     1749314.665      239183.697
     1749801.724      239042.941
#Sta/Elev= 30
       0 1108.78    20.7 1111.54    46.1 1117.06    58.8 1118.20   109.1 1116.59
   282.0 1098.68   307.8 1093.50   340.8 1089.10   483.8 1082.77   573.9 1076.59
   671.8 1063.17   769.4 1051.70   909.2  1056.5   951.3 1055.72   983.3 1050.12
  1011.5 1041.13  1045.8 1032.26  1084.6 1024.93  1626.1 1019.50  1634.4 1019.47
  1641.1 1021.21  1671.0 1033.51  1716.5 1047.46  1792.1 1060.46  1811.9 1068.80
  1895.4 1099.58  1938.6 1113.19  2019.4 1133.45  2049.1 1138.64  2138.1 1147.43
#Mann= 3 , 0 , 0
       0     0.1       0  1626.1   0.045       0  1641.1     0.1       0
Bank Sta=  1626.1,  1641.1
Exp/Cntr=0.3,0.1

Type RM Length L Ch R = 1 ,6503.8,666.363,652.029,647.959
XS GIS Cut Line= 3
     1748141.820      240280.153     1749341.476      239733.313
     1749884.390      239239.552
#Sta/Elev= 30
       0 1036.25    58.4 1034.34    91.5 1031.79   119.2 1035.80   130.6 1040.77
   141.1 1043.30   482.9 1055.72   554.1 1065.48   580.2 1066.92   671.2 1064.98
   778.0 1076.26   883.2 1081.45   911.9 1081.24  1070.1 1072.43  1116.7 1065.49
  1218.4 1047.28  1263.2 1034.47  1288.3 1022.84  1311.7 1019.49  1312.3 1019.49
  1327.3 1019.49  1622.7 1022.76  1651.6 1024.91  1688.9 1038.05  1711.2 1043.71
  1785.7 1056.00  1817.3 1064.14  1919.2 1101.31  1987.7 1123.72  2052.3 1139.07
#Mann= 3 , 0 , 0
       0     0.1       0  1312.3   0.045       0  1327.3     0.1       0
Bank Sta=  1312.3,  1327.3
Exp/Cntr=0.3,0.1

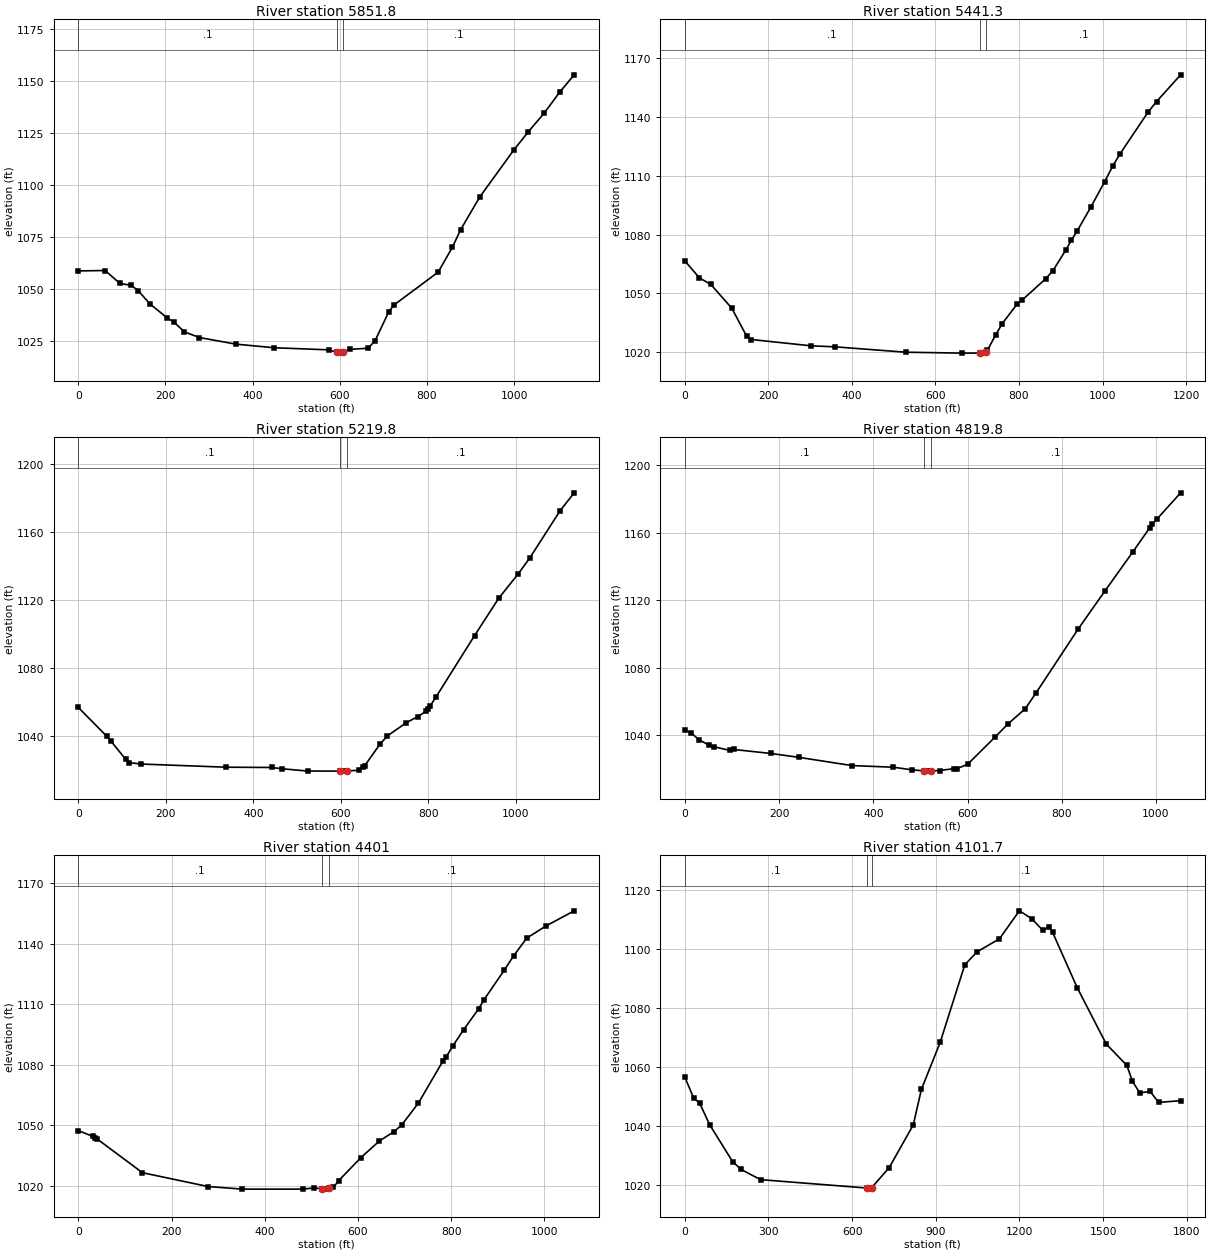
Type RM Length L Ch R = 1 ,5851.8,415.73,410.524,403.741
XS GIS Cut Line= 3
     1749509.042      240303.038     1749770.445      239764.592
     1750040.785      239297.642
#Sta/Elev= 30
       0 1058.92    61.5 1059.11    95.3 1052.93   121.4 1051.96   137.2 1049.48
   164.1 1043.10   203.6 1036.39   219.8 1034.20   243.5 1029.62   277.7 1026.91
   361.8 1023.72   450.1 1021.99   575.2 1020.98     593 1019.84   599.8 1019.41
     608 1020.04   623.2 1021.22   664.8 1021.77   680.7 1025.26   712.5 1039.31
   724.5 1042.58   825.7 1058.32   858.6 1070.37   877.3 1078.75   921.3 1094.48
   999.3 1117.03  1032.2 1125.67  1068.6 1134.64  1105.0 1144.93  1137.8 1153.15
#Mann= 3 , 0 , 0
       0     0.1       0     593   0.045       0     608     0.1       0
Bank Sta=     593,     608
Exp/Cntr=0.3,0.1

Type RM Length L Ch R = 1 ,5441.3,220.554,221.466,220.852
XS GIS Cut Line= 3
     1749940.245      240510.820     1750053.117      239829.056
     1750148.027      239342.326
#Sta/Elev= 30
       0 1066.63    35.1 1057.90    62.1 1054.61   112.6 1042.41   147.8 1028.21
   159.5 1026.44   302.0 1023.23   359.2 1022.71   529.0 1019.96   663.8 1019.49
   705.8 1019.54   713.6 1019.56   720.8 1020.27   724.1 1020.84   744.1 1028.80
   759.9 1034.57   795.3 1044.48   806.7 1046.42   864.3 1057.55   881.4 1061.64
   911.7 1072.04   925.2 1077.05   939.4 1081.94   972.1 1094.10  1004.8 1106.96
  1024.2 1114.96  1041.2 1121.05  1109.7 1142.83  1129.3 1147.98  1186.9 1161.63
#Mann= 3 , 0 , 0
       0     0.1       0   705.8   0.045       0   720.8     0.1       0
Bank Sta=   705.8,   720.8
Exp/Cntr=0.3,0.1

Type RM Length L Ch R = 1 ,5219.8,414.287,400,390.139
XS GIS Cut Line= 3
     1750117.288      240492.074     1750255.397      239902.269
     1750340.940      239382.125
#Sta/Elev= 30
       0 1056.86    64.8 1040.00    74.6 1037.11   108.0 1026.45   116.8 1024.47
   142.5 1023.66   338.3 1021.79   441.9 1021.63   464.9 1020.89   523.8 1019.54
   598.3 1019.50   605.8 1019.49   613.3 1019.61   640.7 1019.97   650.4 1021.74
   654.6 1022.73   689.4 1035.41   706.4 1040.20   748.6 1047.78   775.7 1051.54
   795.5 1054.77   799.2 1055.67   803.9 1057.78   817.5 1063.12   905.4 1099.08
   960.4 1120.93  1005.2 1135.34  1032.2 1144.88  1100.6 1172.31  1132.9 1182.87
#Mann= 3 , 0 , 0
       0     0.1       0   598.3   0.045       0   613.3     0.1       0
Bank Sta=   598.3,   613.3
Exp/Cntr=0.3,0.1

Type RM Length L Ch R = 1 ,4819.8,408.63,418.807,424.669
XS GIS Cut Line= 3
     1750818.293      240362.943     1750608.927      239891.379
     1750445.304      239380.559
#Sta/Elev= 30
       0 1043.05    12.4 1041.70    29.9 1037.55    52.2 1034.14    61.1 1033.34
    95.0 1031.22   103.8 1031.72   181.9 1029.39   241.8 1027.08   354.7 1022.19
   442.5 1021.23   482.1 1019.68   508.5 1019.04   513.9 1018.91   523.5 1019.04
   540.7 1019.28   570.4 1020.34   578.1 1020.44   600.2 1022.95   658.6 1039.10
   685.1 1046.62   722.8 1055.91   745.7 1065.29   835.3 1103.18   891.6 1125.48
   950.9 1148.63   986.6 1162.85   992.2 1164.88  1003.0 1168.34  1052.3 1183.57
#Mann= 3 , 0 , 0
       0     0.1       0   508.5   0.045       0   523.5     0.1       0
Bank Sta=   508.5,   523.5
Exp/Cntr=0.3,0.1

Type RM Length L Ch R = 1 ,4401,293.383,299.353,300.573
XS GIS Cut Line= 3
     1750922.190      240341.639     1750967.983      239820.448
     1750965.997      239279.838
#Sta/Elev= 30
       0 1047.44    31.1 1044.61    36.0 1043.72    39.8 1043.41   137.6 1026.62
   278.2 1019.78   351.6 1018.49   482.2 1018.49   506.3 1019.09   522.9 1018.66
   529.3 1018.49   537.9 1018.88   547.2 1019.33   558.9 1022.76   606.4 1034.13
   646.0 1042.33   677.4 1046.96   693.4 1050.16   729.2 1060.93   782.0 1081.80
   788.7 1083.79   804.1 1089.59   827.0 1097.51   858.8 1107.73   870.4 1112.28
   913.5 1126.75   934.1 1134.05   962.2 1142.77  1002.7 1148.68  1063.8 1156.26
#Mann= 3 , 0 , 0
       0     0.1       0   522.9   0.045       0   537.9     0.1       0
Bank Sta=   522.9,   537.9
Exp/Cntr=0.3,0.1

Type RM Length L Ch R = 1 ,4101.7,337.046,344.286,353.767
XS GIS Cut Line= 3
     1751021.900      240348.704     1751251.728      239731.079
     1751313.769      238613.597
#Sta/Elev= 30
       0 1056.47    31.7 1049.40    53.4 1047.62    89.0 1040.37   171.1 1027.87
   201.9 1025.18   271.8 1021.73   654.9 1018.88   664.7 1018.52   669.9 1018.97
   733.2 1025.84   819.4 1040.27   848.5 1052.30   916.0 1068.27  1004.1 1094.48
  1048.0 1098.88  1128.5 1103.32  1199.8 1112.78  1243.7 1110.17  1283.1 1106.27
  1306.8 1107.24  1318.7 1105.57  1407.6 1086.70  1511.5 1067.66  1585.3 1060.43
  1605.3 1055.08  1631.6 1051.10  1668.7 1051.62  1699.2 1047.90  1778.2 1048.47
#Mann= 3 , 0 , 0
       0     0.1       0   654.9   0.045       0   669.9     0.1       0
Bank Sta=   654.9,   669.9
Exp/Cntr=0.3,0.1

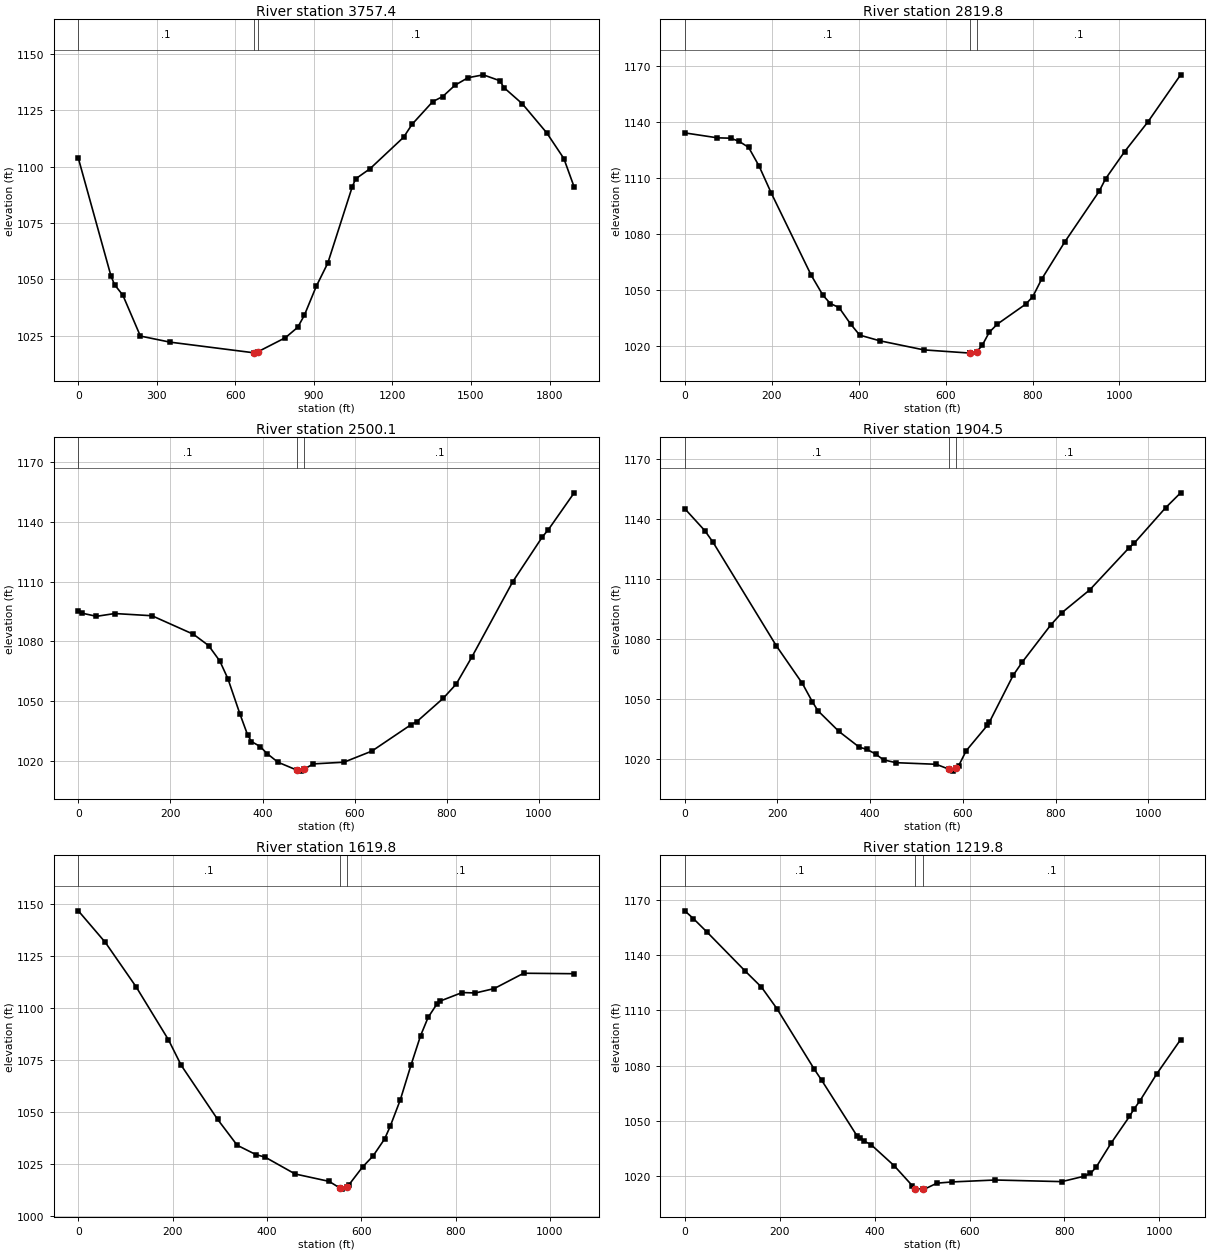
Type RM Length L Ch R = 1 ,3757.4,934.843,937.555,951.218
XS GIS Cut Line= 3
     1751200.342      240450.496     1751539.942      239862.898
     1752009.694      238741.794
#Sta/Elev= 30
       0 1103.68   124.5 1051.62   138.2 1047.71   170.0 1043.04   237.0 1024.92
   350.0 1022.23   670.3 1017.51   678.7 1017.36   685.3 1017.92   791.0 1024.19
   838.2 1028.81   863.6 1034.16   908.9 1046.92   953.1 1057.26  1046.6 1091.08
  1059.5 1094.55  1114.2 1099.01  1242.6 1112.96  1275.2 1118.73  1354.0 1128.75
  1391.9 1130.98  1438.7 1135.98  1488.4 1139.32  1547.1 1140.61  1610.7 1137.98
  1625.6 1134.98  1696.1 1127.79  1789.3 1114.93  1854.8 1103.55  1894.2 1090.92
#Mann= 3 , 0 , 0
       0     0.1       0   670.3   0.045       0   685.3     0.1       0
Bank Sta=   670.3,   685.3
Exp/Cntr=0.3,0.1

Type RM Length L Ch R = 1 ,2819.8,316.186,319.765,316.878
XS GIS Cut Line= 3
     1751426.270      240760.989     1751837.254      240239.586
     1752230.305      239969.558
#Sta/Elev= 30
       0 1134.32    75.1 1131.67   105.2 1131.48   124.4 1129.85   146.8 1126.56
   171.1 1116.42   198.9 1102.02   290.7 1057.93   317.9 1047.11   334.8 1042.69
   354.9 1040.50   381.4 1031.69   402.4 1025.72   448.2 1022.69   549.7 1017.79
   656.4 1016.05   657.0 1016.04   671.4 1016.66   684.4 1020.28   700.5 1027.24
   718.9 1031.59   784.0 1042.28   800.3 1046.22   820.8 1055.68   874.2 1075.75
   953.3 1102.94   968.1 1109.67  1012.0 1124.28  1065.8 1140.32  1140.8 1165.51
#Mann= 3 , 0 , 0
       0     0.1       0   656.4   0.045       0   671.4     0.1       0
Bank Sta=   656.4,   671.4
Exp/Cntr=0.3,0.1

Type RM Length L Ch R = 1 ,2500.1,605.895,595.528,580.285
XS GIS Cut Line= 3
     1751511.030      240871.164     1751867.554      240543.365
     1752333.199      240177.646
#Sta/Elev= 30
       0 1095.03     8.9 1094.06    39.4 1092.52    79.1 1093.92   159.9 1092.81
   249.9 1083.50   282.7 1077.86   307.1 1070.10   324.7 1061.20   350.7 1043.58
   367.5 1032.97   375.9 1029.66   394.8 1027.12   409.6 1023.64   433.2 1019.30
   475.7 1015.19   483.4 1014.80   490.7 1015.89   510.3 1018.43   576.6 1019.28
   637.2 1024.85   722.1 1038.09   735.1 1039.70   792.3 1051.41   820.3 1058.49
   854.5 1072.17   942.9 1109.82  1007.5 1132.44  1020.6 1136.09  1076.4 1154.52
#Mann= 3 , 0 , 0
       0     0.1       0   475.7   0.045       0   490.7     0.1       0
Bank Sta=   475.7,   490.7
Exp/Cntr=0.3,0.1

Type RM Length L Ch R = 1 ,1904.5,277.615,284.707,288.498
XS GIS Cut Line= 3
     1752071.625      241310.055     1752288.404      240774.457
     1752443.670      240307.552
#Sta/Elev= 30
       0 1145.01    43.3 1134.01    61.0 1128.21   197.4 1076.51   253.7 1057.67
   275.1 1048.58   287.1 1044.08   332.7 1033.67   376.3 1025.85   392.9 1024.73
   411.6 1022.42   428.8 1019.50   455.7 1018.08   542.4 1017.28   570.5 1014.78
   578.9 1013.86   585.5 1015.33   591.1 1016.63   607.1 1024.04   652.9 1036.77
   657.4 1038.43   708.6 1061.79   728.1 1068.34   789.6 1086.90   813.7 1093.06
   873.8 1104.46   958.4 1125.44   970.2 1127.92  1037.2 1145.44  1069.8 1152.94
#Mann= 3 , 0 , 0
       0     0.1       0   570.5   0.045       0   585.5     0.1       0
Bank Sta=   570.5,   585.5
Exp/Cntr=0.3,0.1

Type RM Length L Ch R = 1 ,1619.8,392.153,400,410.684
XS GIS Cut Line= 3
     1752166.706      241363.072     1752525.470      240931.045
     1752752.627      240497.192
#Sta/Elev= 30
       0 1146.59    57.3 1131.43   122.5 1110.15   191.1 1084.74   218.2 1072.48
   295.5 1046.52   336.8 1034.17   376.4 1029.69   396.1 1028.45   459.7 1020.38
   531.7 1016.84   554.1 1013.72   559.0 1013.12   569.1 1014.25   573.4 1015.09
   602.9 1023.81   624.7 1028.96   649.4 1037.17   661.3 1043.26   682.7 1055.95
   705.3 1072.56   725.6 1086.67   741.6 1095.46   760.9 1102.11   766.9 1103.29
   813.8 1107.40   842.0 1107.19   881.8 1109.30   944.2 1116.66  1051.3 1116.43
#Mann= 3 , 0 , 0
       0     0.1       0   554.1   0.045       0   569.1     0.1       0
Bank Sta=   554.1,   569.1
Exp/Cntr=0.3,0.1

Type RM Length L Ch R = 1 ,1219.8,479.235,494.127,510.781
XS GIS Cut Line= 3
     1752262.586      241513.789     1752689.755      241266.737
     1753141.791      240951.114
#Sta/Elev= 30
       0 1164.00    18.1 1159.78    47.1 1152.40   127.8 1131.18   161.6 1122.60
   194.1 1110.93   272.9 1078.06   288.3 1072.12   363.2 1041.77   369.4 1040.92
   378.5 1038.95   392.3 1037.18   441.3 1025.68   479.1 1014.96     486 1013.26
     501 1013.07   505.0 1013.01   531.4 1016.25   563.0 1016.91   654.2 1017.96
   794.4 1017.08   841.2 1019.99   854.8 1021.50   866.7 1024.88   897.8 1037.77
   937.0 1052.44   946.1 1056.29   959.2 1060.98   994.0 1075.36  1044.8 1094.14
#Mann= 3 , 0 , 0
       0     0.1       0     486   0.045       0     501     0.1       0
Bank Sta=     486,     501
Exp/Cntr=0.3,0.1

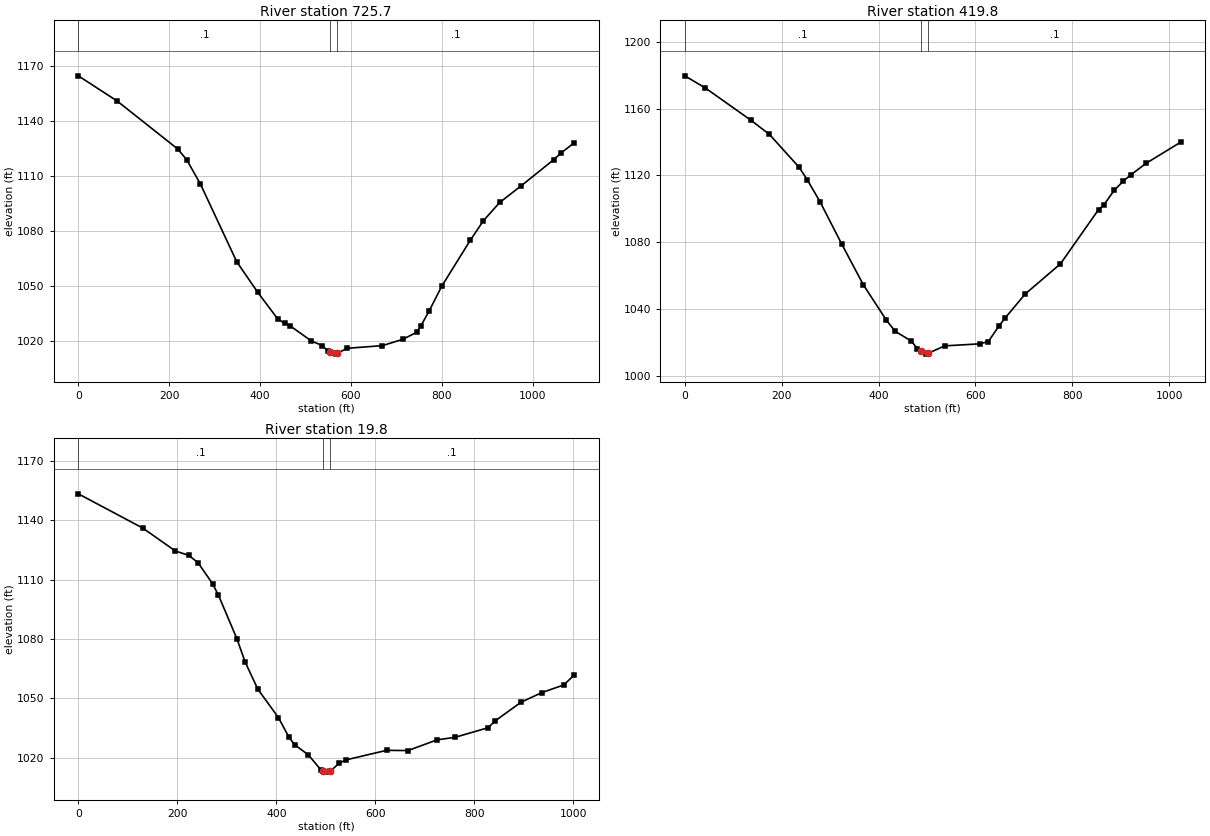
Type RM Length L Ch R = 1 ,725.7,302.633,305.873,314.119
XS GIS Cut Line= 3
     1752274.998      241534.090     1752835.786      241612.287
     1753356.691      241679.145
#Sta/Elev= 30
       0 1164.68    85.2 1150.99   218.4 1124.87   238.4 1119.00   268.5 1105.81
   348.7 1063.31   394.7 1046.74   438.9 1032.15   454.2 1029.71   465.2 1028.57
   512.5 1020.22   537.3 1017.58   550.1 1014.47   554.5 1014.24   566.2 1012.97
   569.5 1013.42   592.3 1016.16   669.3 1017.60   714.1 1021.04   744.4 1024.82
   754.2 1028.49   772.4 1036.58   799.7 1049.89   862.6 1074.97   891.5 1085.65
   927.5 1095.63   974.5 1104.67  1046.7 1119.02  1062.8 1122.67  1091.4 1128.14
#Mann= 3 , 0 , 0
       0     0.1       0   554.5   0.045       0   569.5     0.1       0
Bank Sta=   554.5,   569.5
Exp/Cntr=0.3,0.1

Type RM Length L Ch R = 1 ,419.8,397.024,400,398.052
XS GIS Cut Line= 3
     1752269.824      241727.043     1752751.504      241843.670
     1753227.769      242072.240
#Sta/Elev= 30
       0 1179.74    42.7 1172.40   137.0 1153.01   174.9 1144.57   236.0 1124.91
   253.0 1117.38   279.4 1104.15   323.7 1079.06   368.6 1054.49   416.5 1033.10
   434.7 1026.47   467.9 1020.69   480.3 1016.14   488.1 1014.78   498.8 1012.85
   503.1 1013.43   536.6 1017.80   608.7 1019.01   626.7 1020.35   648.7 1029.68
   660.7 1034.25   703.1 1048.95   775.8 1067.01   854.5 1099.55   865.3 1102.29
   887.2 1111.28   905.8 1116.65   920.5 1120.24   953.2 1127.39  1023.9 1139.94
#Mann= 3 , 0 , 0
       0     0.1       0   488.1   0.045       0   503.1     0.1       0
Bank Sta=   488.1,   503.1
Exp/Cntr=0.3,0.1

Type RM Length L Ch R = 1 ,19.8,18.316,19.816,21.446
XS GIS Cut Line= 3
     1752208.530      242054.051     1752676.216      242235.146
     1753143.814      242413.110
#Sta/Elev= 30
       0 1153.45   130.0 1136.16   196.2 1124.53   222.6 1122.40   241.7 1118.70
   271.1 1108.04   283.1 1102.20   320.3 1080.24   337.2 1068.31   362.7 1054.69
   404.4 1040.28   425.7 1030.30   437.2 1026.57   464.5 1021.54   490.0 1013.93
     494 1013.44   502.7 1012.75     509 1013.19   527.1 1017.29   540.8 1018.94
   622.9 1023.77   666.0 1023.65   724.7 1029.06   761.4 1030.37   827.8 1035.20
   842.4 1038.69   894.3 1048.07   936.7 1052.98   980.7 1056.81  1001.8 1061.82
#Mann= 3 , 0 , 0
       0     0.1       0     494   0.045       0     509     0.1       0
Bank Sta=     494,     509
Exp/Cntr=0.3,0.1